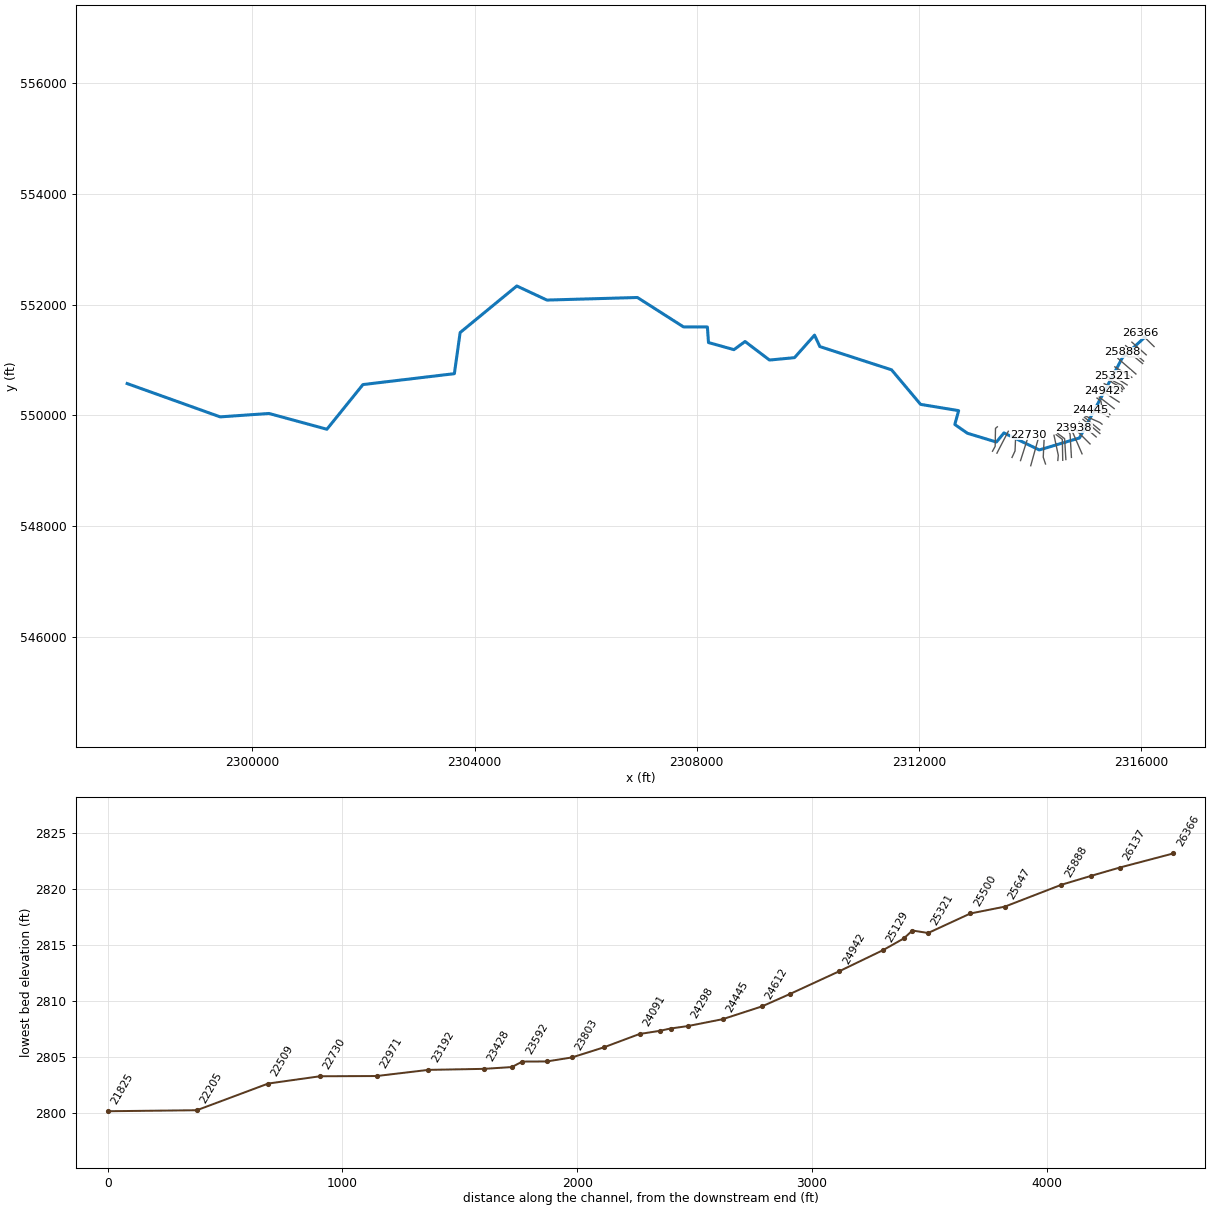
--- BRSHRN.prj (project) ---

Proj Title=BRSHRN
Current Plan=p01
Default Exp/Contr=0,0
English Units
Geom File=g01
Flow File=f01
Plan File=p01
BEGIN DESCRIPTION:
----------MODEL BY WOOD PLC 2021----------
Stream Name: Brush Run
Flood Zone: Enhanced Approximate
Pocahontas County, WV
HEC-RAS Version: RAS 6.0
Vertical Datum: NAVD88
Projection: NAD 1983 StatePlane West Virginia S FIPS 4702 (US Feet)
Terrain: 1-meter LIDAR (FEMA Region III 3DEP collected 2016-2018)
Land Use: 2019 NLCD
Hydrologic Method:
WV SIR2010-5033 regression equations weighted with gage 03180530
END DESCRIPTION:
DSS Export Rating Curves= 0
DSS Export Rating Curve Sorted= 0
DSS Export Volume Flow Curves= 0
DXF OffsetX= 0
DXF OffsetY= 0
DXF ScaleX= 0
DXF ScaleY= 0

--- BRSHRN.p01 (plan) ---

Plan Title=Floodplain
Program Version=4.00
Geom File=g01
Flow File=f01
K Sum by GR=0
Std Step Tol=0.01
Critical Tol=0.01
Num of Std Step Trials=20
Max Error Tol=0.3
Flow Tol Ratio=0.001
Split Flow NTrial=30
Split Flow Tol=0.02
Split Flow Ratio=0.02
Log Output Level=0
Friction Slope Method=1
Unsteady Friction Slope Method=2
Unsteady Bridges Friction Slope Method=1
Global Log Level=0
CheckData=False
Run HTab=0
Run UNet=0
Run PostProcess=0
UNET Theta=0
UNET Theta Warmup=0
UNET ZTol=0
UNET ZSATol=0
UNET MxIter=0
UNET MaxInSteps=0
UNET DtIC=0
UNET DtMin=0
UNET MaxCRTS=0
UNET WFStab=0
UNET SFStab=0
UNET WFX=0
UNET SFX=0
UNET DSS MLevel=0
UNET DZMax Abort=0
UNET Convert EG Bridges=0
UNET Use Existing IB Tables=0
UNET Froude Limit=0
UNET Froude Power=0
Write IC File=0
Echo Input=False
Echo Output=False
Write Detailed=0

--- BRSHRN.f01 (steady flow) ---

Flow Title=Flow
Program Version=6.10
Number of Profiles= 6
Profile Names=01pct,10pct,04pct,02pct,0_2pct,01plus
River Rch & RM=BRSHRN,Main,26366
     692     328     457     568    1040    1290
River Rch & RM=BRSHRN,Main,18614
     797     387     533     658    1180    1440
River Rch & RM=BRSHRN,Main,16238
    1050     528     716     874    1520    1800
River Rch & RM=BRSHRN,Main,14693
    1240     635     853    1040    1770    2060
River Rch & RM=BRSHRN,Main,9188
    1380     716     956    1160    1960    2260
River Rch & RM=BRSHRN,Main,4121
    1560     820    1090    1310    2200    2520
Boundary for River Rch & Prof#=BRSHRN,Main            , 1
Up Type= 0
Dn Type= 3
Dn Slope=0.01518
Boundary for River Rch & Prof#=BRSHRN,Main            , 2
Up Type= 0
Dn Type= 3
Dn Slope=0.01518
Boundary for River Rch & Prof#=BRSHRN,Main            , 3
Up Type= 0
Dn Type= 3
Dn Slope=0.01518
Boundary for River Rch & Prof#=BRSHRN,Main            , 4
Up Type= 0
Dn Type= 3
Dn Slope=0.01518
Boundary for River Rch & Prof#=BRSHRN,Main            , 5
Up Type= 0
Dn Type= 3
Dn Slope=0.01518
Boundary for River Rch & Prof#=BRSHRN,Main            , 6
Up Type= 0
Dn Type= 3
Dn Slope=0.01518
DSS Import GetInterval= 0
DSS Import GetPeak= 0
DSS Import FillOption= 0

--- BRSHRN.g01 (geometry) ---

Geom Title=Geometry
Program Version=6.10

River Reach=BRSHRN          ,Main
Reach XY= 30
     2316071.639      551411.7372315666.07065007551039.313663649
     2314893.862      549595.071     2314170.392      549379.258
     2313533.946      549685.884     2313397.957      549521.299
     2312875.709      549680.061     2312648.968      549837.987
      2312718.02      550087.326     2312032.496      550200.531
     2311509.938      550822.987     2310218.893      551241.864
     2310122.797      551447.871     2309762.117      551042.251
      2309311.97      550999.015     2308871.891       551333.17
     2308671.674      551186.425     2308213.158      551314.529
     2308193.616      551594.735     2307763.086      551596.523
     2306933.653      552126.286     2305303.455      552079.861
     2304761.185      552333.758     2303740.862      551494.525
     2303637.125      550753.612     2301990.651      550557.204
     2301341.546      549752.156     2300298.934       550036.31
     2299419.544      549975.022     2297744.183      550575.571

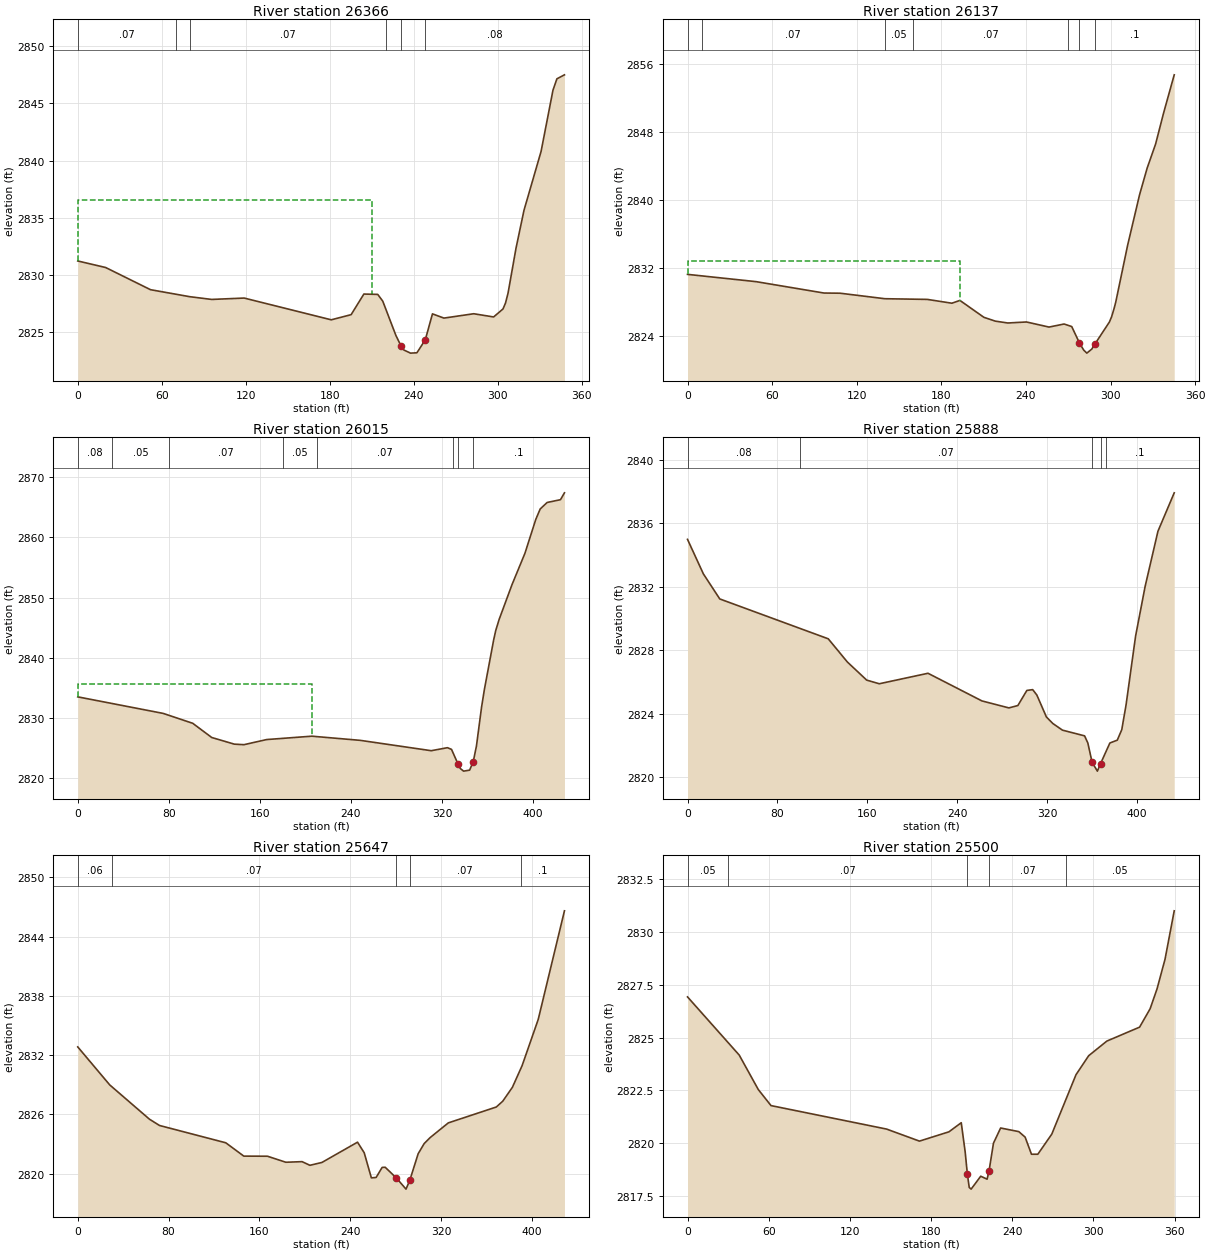
Type RM Length L Ch R = 1 ,26366   ,227.6,228.3,227.1
XS GIS Cut Line= 2
2316237.32740674551242.217849631  2315988.811293551485.378012648
#Sta/Elev= 30
       0 2831.24    19.9 2830.67      52 2828.73      80 2828.12    95.7 2827.88
   118.9    2828   181.1  2826.1   195.3 2826.55   204.4 2828.35   214.3 2828.32
   217.9 2827.73   227.3 2824.73     2312823.805     233 2823.46   237.7 2823.19
   242.3 2823.22   248.32824.357   253.4 2826.62   261.6 2826.25   282.9 2826.63
   297.1 2826.35   303.8 2827.05   305.6 2827.57   307.4 2828.43   313.1 2832.36
   318.8 2835.67     331 2840.81   339.5 2846.16   342.3 2847.15   347.7  2847.5
#Mann= 6 ,-1,0
       0     .07       0      70     .05       0      80     .07       0
     220     .08       0     231    .045       0   248.3     .08       0
#XS Ineff= 2 , 0
          210.34  2836.6
Permanent Ineff=
       F       F
Bank Sta=231,248.3
XS Rating Curve= 0 ,0
Exp/Cntr(USF)=0,0
Exp/Cntr=0.3,0.1

Type RM Length L Ch R = 1 ,26137   ,121.9,122.1,122.6
XS GIS Cut Line= 2
2316095.93030754551092.2512292692315837.77348249551321.485920394
#Sta/Elev= 30
       0 2831.21    48.7 2830.35    96.8 2829.01   108.2 2828.99     140 2828.34
   170.1 2828.26   187.5 2827.81   193.2 2828.14   210.2 2826.15   218.3  2825.7
   227.2 2825.48   240.4  2825.6   256.4    2825   267.1 2825.36   272.5 2825.06
     2782823.125     281 2822.29   283.2 2821.93   286.7  2822.4   289.22823.062
   299.2 2825.59   300.8 2826.22   302.6 2827.22   303.7 2827.92   312.2 2834.68
   320.6 2840.58     326 2843.73     332 2846.57   337.7 2850.25   345.2 2854.72
#Mann= 7 ,-1,0
       0     .08       0      10     .07       0     140     .05       0
     160     .07       0     270      .1       0     278    .045       0
   289.2      .1       0
#XS Ineff= 2 , 0
          192.92 2832.84
Permanent Ineff=
       F       F
Bank Sta=278,289.2
XS Rating Curve= 0 ,0
Exp/Cntr(USF)=0,0
Exp/Cntr=0.3,0.1

Type RM Length L Ch R = 1 ,26015   ,127.3,127.3,128.5
XS GIS Cut Line= 2
2316048.56190451550979.5809643152315725.13425542551259.104407647
#Sta/Elev= 30
       0 2833.52    75.1 2830.77     101 2829.13   117.7 2826.77   137.5 2825.67
     146 2825.58   165.9 2826.43   205.6 2826.99   248.1  2826.3   310.5 2824.58
   324.7 2825.08   328.3  2824.8   334.12822.327     336 2821.63   338.9 2821.19
   344.2 2821.35   347.4 2822.78   350.2 2825.36   354.7 2831.83   357.2 2834.77
   365.3 2842.96   367.2 2844.57   370.1 2846.36   381.4 2852.13   392.8 2857.36
   402.3 2862.97   406.2 2864.71   412.3 2865.79     424 2866.25   427.5 2867.39
#Mann= 8 ,-1,0
       0     .08       0      30     .05       0      80     .07       0
     180     .05       0     210     .07       0     330      .1       0
   334.1    .045       0   347.4      .1       0
#XS Ineff= 2 , 0
          205.32 2835.58
Permanent Ineff=
       F       F
Bank Sta=334.1,347.4
XS Rating Curve= 0 ,0
Exp/Cntr(USF)=0,0
Exp/Cntr=0.3,0.1

Type RM Length L Ch R = 1 ,25888   ,232.4,240.9,239.5
XS GIS Cut Line= 4
2316031.05647164550935.706861238 2315886.1163432551055.681587631
2315771.96540823 551052.754640582315672.81020009551138.312405523
#Sta/Elev= 30
       0 2834.98    14.1 2832.81    28.7 2831.23   125.3 2828.72   142.3 2827.26
   159.5 2826.12   170.7 2825.89   214.1 2826.55   262.1 2824.81   286.1 2824.37
   294.1 2824.52   302.1 2825.47   307.3 2825.52     311 2825.18   319.5  2823.8
   325.2 2823.39   333.8 2822.97   353.5 2822.61   356.4 2822.16   360.2 2820.94
   364.9 2820.39   367.7 2820.86     376 2822.16   382.6 2822.34   386.6    2823
   390.4 2824.55   398.9 2828.89   407.4 2832.02   418.8 2835.49   433.3 2837.91
#Mann= 5 ,-1,0
       0     .08       0     100     .07       0   360.2    .045       0
   367.7     .07       0  372.34      .1       0
Bank Sta=360.2,367.7
XS Rating Curve= 0 ,0
Exp/Cntr(USF)=0,0
Exp/Cntr=0.3,0.1

Type RM Length L Ch R = 1 ,25647   ,145.2,146.6,147.7
XS GIS Cut Line= 2
2315910.59434606 550747.774162692315586.88912882551028.579809654
#Sta/Elev= 30
       0 2832.83    28.2 2828.98    63.2 2825.51      72 2824.88   130.3 2823.13
   146.2 2821.78     167 2821.77   183.2 2821.16   197.5 2821.22   204.4 2820.85
     215 2821.14   246.3 2823.19   252.2 2822.12   258.5 2819.58   262.7 2819.62
     268 2820.64   270.7 2820.65   280.6 2819.56     289 2818.44   292.42819.358
   299.7 2822.02     305 2823.05   310.3 2823.66   326.2 2825.14   368.5 2826.75
   374.2 2827.34   382.7 2828.75   391.2 2830.93   405.4 2835.61   428.5  2846.6
#Mann= 5 ,-1,0
       0     .06       0      30     .07       0   280.6    .045       0
   292.4     .07       0     390      .1       0
Bank Sta=280.6,292.4
XS Rating Curve= 0 ,0
Exp/Cntr(USF)=0,0
Exp/Cntr=0.3,0.1

Type RM Length L Ch R = 1 ,25500   ,178.3,179.9,179
XS GIS Cut Line= 2
2315836.70229234550687.3413542892315530.34191075550875.870819888
#Sta/Elev= 30
       0 2826.92    38.2 2824.17    52.3 2822.54    61.7 2821.78   147.1 2820.67
   171.4  2820.1   193.2 2820.54   202.3 2820.97   205.2 2819.59  206.83 2818.53
   208.2 2817.91   209.6 2817.83   216.7 2818.44   221.4  2818.3   222.82818.673
   226.1    2820   231.4 2820.72   244.8 2820.55   249.5 2820.29   254.2 2819.48
   258.9 2819.48   269.2 2820.43   287.1 2823.24   296.5 2824.14   309.9 2824.83
   334.1 2825.49   341.9 2826.36     347  2827.3   352.9  2828.7   359.7 2830.99
#Mann= 5 ,-1,0
       0     .05       0      30     .07       0  206.83    .045       0
   222.8     .07       0     280     .05       0
Bank Sta=206.83,222.8
XS Rating Curve= 0 ,0
Exp/Cntr(USF)=0,0
Exp/Cntr=0.3,0.1

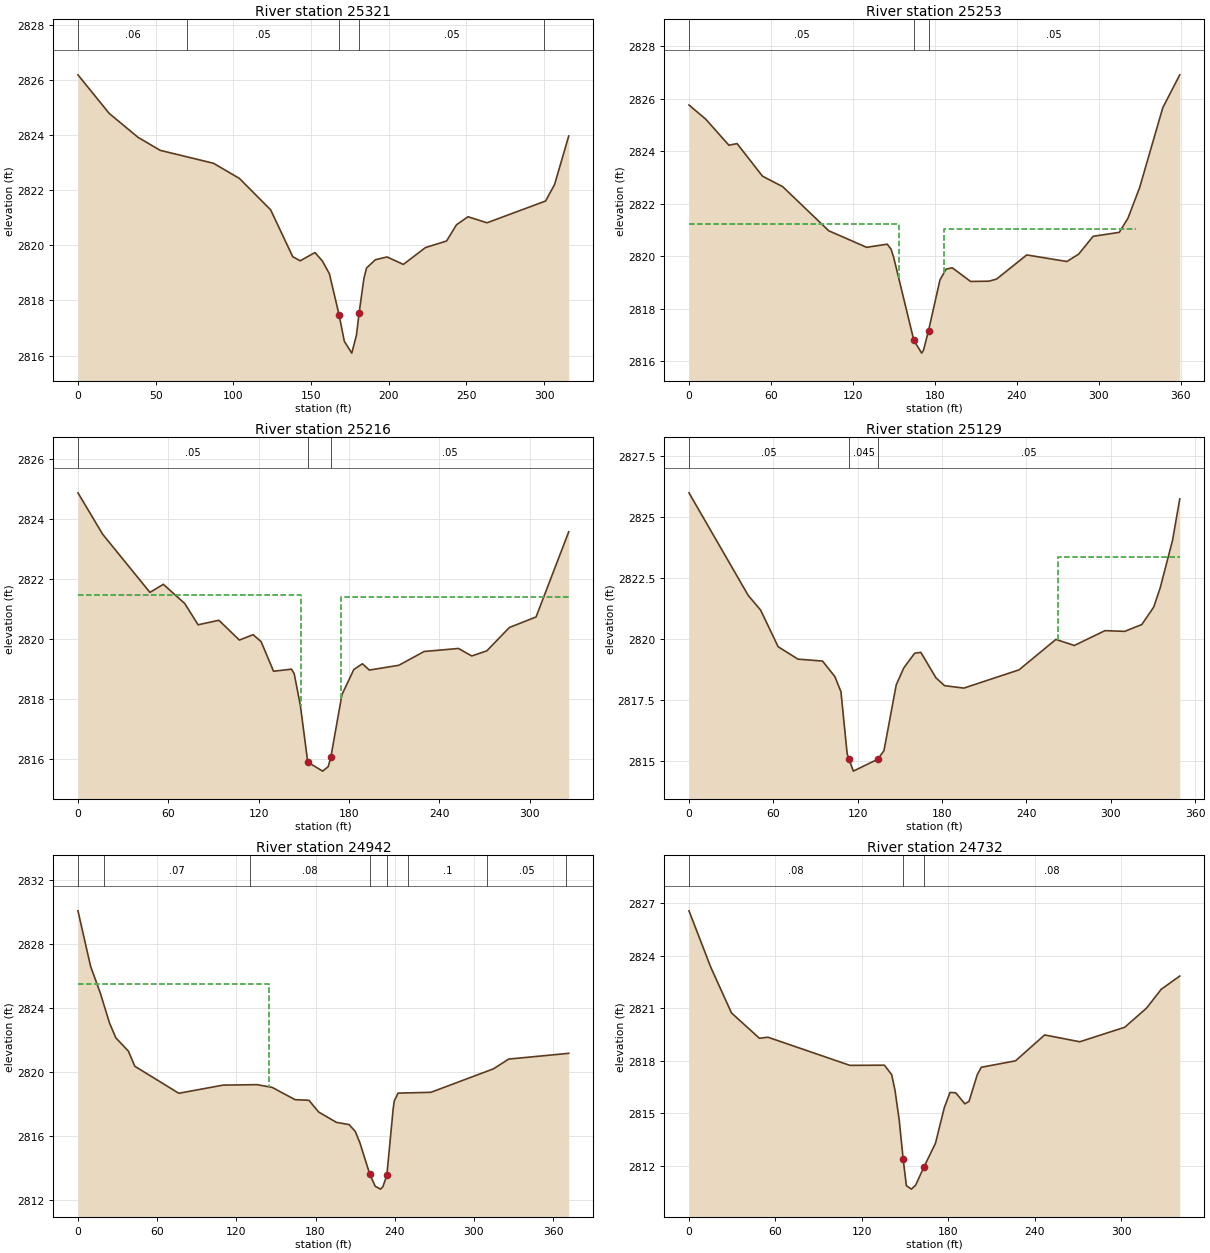
Type RM Length L Ch R = 1 ,25321   ,65.9,67.1,68
XS GIS Cut Line= 2
2315752.78943484550550.3767142452315486.36903338550719.963546711
#Sta/Elev= 30
       0 2826.19    20.1 2824.79    38.7 2823.92    52.9 2823.45    87.2 2822.98
   103.9 2822.43     124 2821.29   138.2 2819.59     143 2819.44   152.5 2819.74
   157.2 2819.44   161.8 2818.97     1682817.488   171.4 2816.52   176.2 2816.09
   179.2 2816.74   180.9 2817.54     184  2818.8   185.7 2819.18   191.4 2819.48
   198.9 2819.58   209.4 2819.31   223.6 2819.92   237.2 2820.16   243.6 2820.75
     251 2821.04   263.2 2820.82   300.9 2821.61   306.7 2822.21   315.8 2823.97
#Mann= 5 ,-1,0
       0     .06       0      70     .05       0     168    .045       0
   180.9     .05       0     300     .07       0
Bank Sta=168,180.9
XS Rating Curve= 0 ,0
Exp/Cntr(USF)=0,0
Exp/Cntr=0.5,0.3

Type RM Length L Ch R = 1 ,25253   ,37.6,37.1,37.4
XS GIS Cut Line= 4
2315697.58529216550485.4415547562315655.06975529 550544.76149928
2315517.61292534550613.9916631362315414.53315783550696.933241029
#Sta/Elev= 30
       0 2825.76    12.3 2825.22    29.2 2824.23    35.2 2824.29    53.8 2823.05
    68.6 2822.65   102.3 2820.97     130 2820.34   145.1 2820.46   147.9 2820.27
   149.9 2819.94   164.62816.795   170.3 2816.31   171.7 2816.43   175.32817.164
   183.7  2819.1   188.2 2819.51   192.7 2819.56   206.1 2819.04   219.5 2819.05
   225.1 2819.13   247.2 2820.05   276.6  2819.8   285.2 2820.08   295.8 2820.76
   314.9 2820.91   321.3 2821.45   329.8 2822.61   346.8 2825.66   359.2 2826.91
#Mann= 3 ,-1,0
       0     .05       0   164.6    .045       0   175.3     .05       0
#XS Ineff= 2 ,-1
       0  153.57 2821.23  186.37   327.32821.019
Permanent Ineff=
       F       F
Bank Sta=164.6,175.3
XS Rating Curve= 0 ,0
Exp/Cntr(USF)=0,0
Exp/Cntr=0.5,0.3

Type RM Length L Ch R = 1 ,25216   ,90.2,87.1,91.1
XS GIS Cut Line= 4
2315670.68770761550464.6176183292315632.89996788 550512.54565879
2315498.89023209550584.4023766122315408.65317423550652.033046176
#Sta/Elev= 30
       0 2824.88    16.4  2823.5    47.8 2821.56    56.7 2821.83    70.9 2821.19
    79.8 2820.48    93.6 2820.63   107.2 2819.97   116.3 2820.15   121.6 2819.92
   129.9 2818.93   141.8    2819   143.6 2818.85   147.7 2817.79   152.6  2815.9
   162.5  2815.6   166.2 2815.75167.91742816.062   175.3 2818.15   183.2 2818.99
   188.9 2819.18   193.5 2818.97   213.1 2819.13   229.9 2819.59   252.7 2819.69
   261.5 2819.44   271.5 2819.61   286.5 2820.39   304.2 2820.74   325.9 2823.58
#Mann= 3 ,-1,0
       0     .05       0   152.6    .045       0167.9174     .05       0
#XS Ineff= 2 , 0
          147.79 2821.48  174.82         2821.39
Permanent Ineff=
       F       F
Bank Sta=152.6,167.9174
XS Rating Curve= 0 ,0
Exp/Cntr(USF)=0,0
Exp/Cntr=0.5,0.3

Type RM Length L Ch R = 1 ,25129   ,193.6,187.1,188.8
XS GIS Cut Line= 2
2315659.18807917550432.7006755232315339.45689072550572.946685682
#Sta/Elev= 30
       0    2826    42.1 2821.79      51 2821.18    63.4 2819.68    77.5 2819.17
      95 2819.09   103.8 2818.45   108.1 2817.83   112.5 2815.29   113.9 2815.05
   116.9 2814.57   134.3 2815.06   138.7 2815.41   147.4 2818.11   152.8 2818.81
   160.5 2819.41   164.9 2819.45   175.7  2818.4   181.8 2818.08   195.5 2817.98
   234.8 2818.73     261 2819.98   274.1 2819.73   295.9 2820.34   309.9 2820.31
   322.1 2820.59   330.6 2821.31   335.2  2822.1     344 2824.06   349.1 2825.75
#Mann= 3 ,0,0
       0     .05       0   113.9    .045       0   134.3     .05       0
#XS Ineff= 2 , 0
                          262.75         2823.38
Permanent Ineff=
       F       F
Bank Sta=113.9,134.3
XS Rating Curve= 0 ,0
Exp/Cntr(USF)=0,0
Exp/Cntr=0.3,0.1

Type RM Length L Ch R = 1 ,24942   ,209.8,210.3,207.4
XS GIS Cut Line= 2
2315608.21589833550241.6279657512315296.72451594550444.661345919
#Sta/Elev= 30
       0  2830.1     9.6 2826.62      17 2824.94    23.9 2823.08    28.7 2822.15
    38.2 2821.32    43.1 2820.37    76.4 2818.68   109.9 2819.19   135.6 2819.22
   147.1 2819.05   164.5 2818.28     175 2818.24   182.3 2817.51   195.8 2816.86
   205.4 2816.72   210.1 2816.29   213.6 2815.58   221.1 2813.61   225.2 2812.86
   229.2 2812.68     231 2812.83     234 2813.54   238.8  2817.7   239.6 2818.19
   242.5 2818.69   267.4 2818.74   314.8 2820.21   326.3 2820.82   371.8 2821.18
#Mann= 8 ,-1,0
       0     .06       0      20     .07       0     130     .08       0
   221.1    .045       0     234     .08       0     250      .1       0
     310     .05       0     370      .1       0
#XS Ineff= 2 , 0
          144.54 2825.54
Permanent Ineff=
       F       F
Bank Sta=221.1,234
XS Rating Curve= 0 ,0
Exp/Cntr(USF)=0,0
Exp/Cntr=0.3,0.1

Type RM Length L Ch R = 1 ,24732   ,129.9,119.6,112.3
XS GIS Cut Line= 2
2315519.53110593550123.9028884172315249.97941568550332.268018884
#Sta/Elev= 30
       0 2826.57    15.2 2823.33    29.5 2820.73    48.9 2819.28    54.8 2819.34
   111.7 2817.73   135.7 2817.74   140.7  2817.2     143 2816.31   145.9 2814.63
   148.7 2812.36   150.9 2810.85   154.4 2810.65   157.3 2810.87     163  2811.9
   171.1 2813.27   177.2  2815.3   181.2 2816.18   185.2 2816.16   191.5 2815.53
   194.4 2815.67   200.1 2817.19   202.9 2817.62   226.7 2817.99   246.9 2819.47
   271.3 2819.08   302.5 2819.91   317.7 2821.01   327.8 2822.08   340.7 2822.84
#Mann= 3 ,-1,0
       0     .08       0   148.7    .045       0     163     .08       0
Bank Sta=148.7,163
XS Rating Curve= 0 ,0
Exp/Cntr(USF)=0,0
Exp/Cntr=0.3,0.1

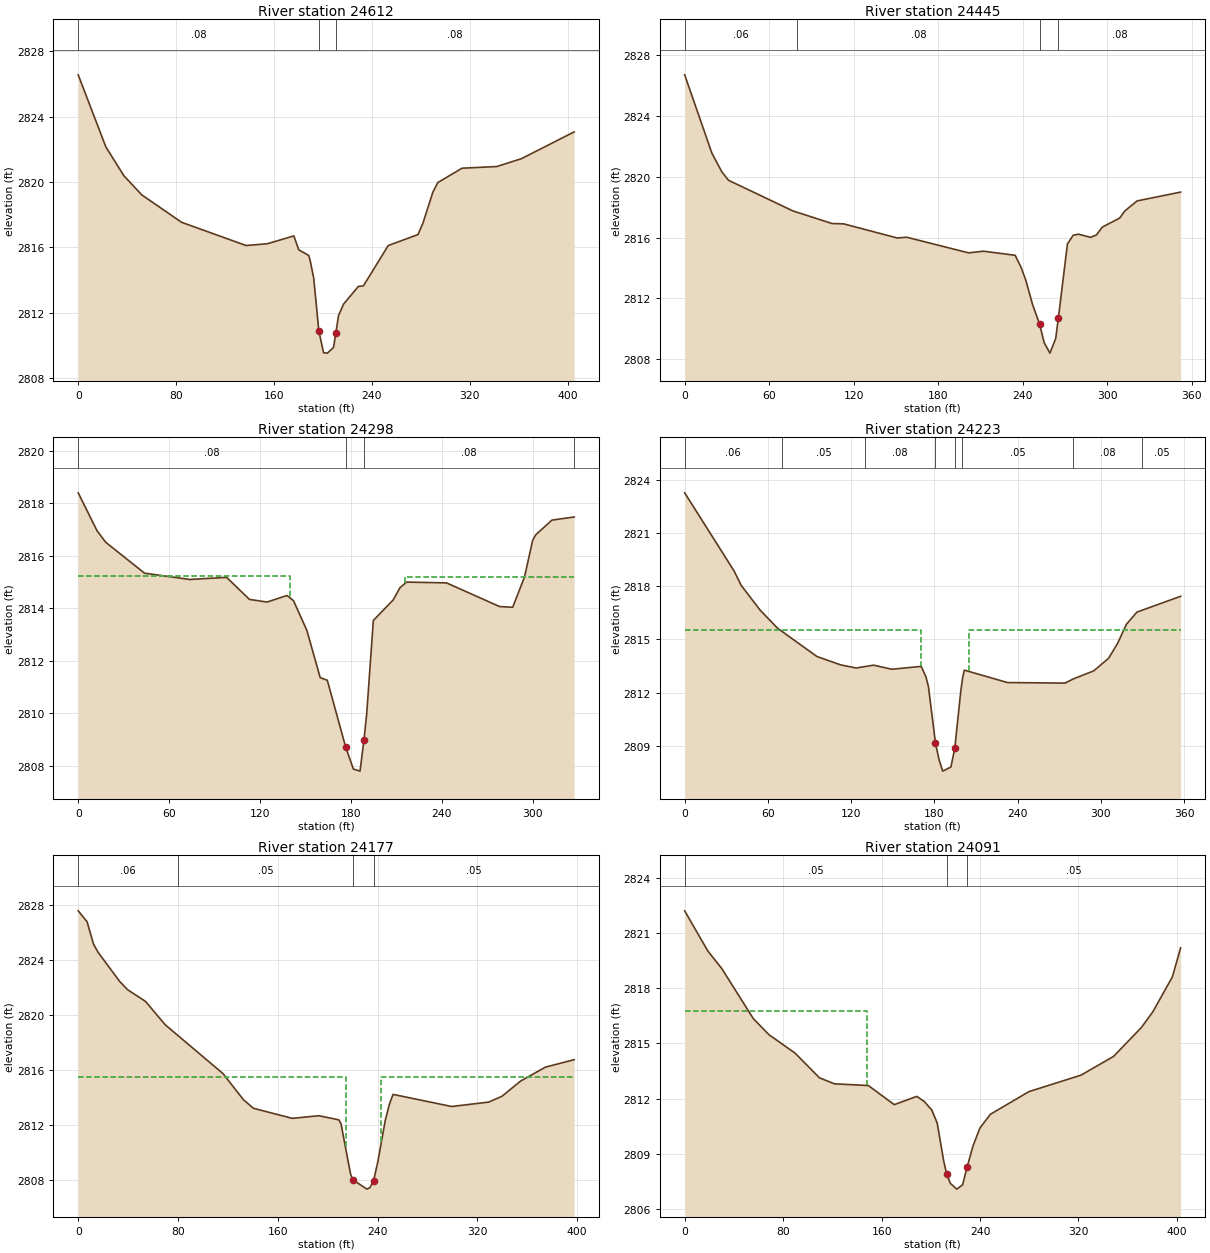
Type RM Length L Ch R = 1 ,24612   ,152.8,167.5,180.1
XS GIS Cut Line= 4
2315442.68386504 550016.615384672315305.11735366550113.204637339
2315280.23830373550259.5519898692315209.99157452550313.700510305
#Sta/Elev= 30
       0 2826.56    22.6 2822.15    37.3 2820.39    51.9 2819.22    84.5 2817.54
   137.2 2816.12   154.6 2816.23   176.2 2816.71   180.2 2815.86   188.4 2815.51
   189.7 2815.14   192.4 2814.14   196.6 2810.89   200.5 2809.56   203.6 2809.54
   208.6 2809.89   210.5 2810.77   212.7 2811.84   216.8 2812.54   228.9 2813.62
     233 2813.65   253.3 2816.12   277.6 2816.79   281.7  2817.5   289.8 2819.39
   293.8 2819.97   313.6 2820.85   341.9 2820.95   362.1 2821.43   405.2 2823.07
#Mann= 3 ,-1,0
       0     .08       0   196.6    .045       0   210.5     .08       0
Bank Sta=196.6,210.5
XS Rating Curve= 0 ,0
Exp/Cntr(USF)=0,0
Exp/Cntr=0.3,0.1

Type RM Length L Ch R = 1 ,24445   ,149.1,147.1,145.1
XS GIS Cut Line= 3
2315419.22582097549973.9375484042315307.13648415550036.859257547
 2315090.2204797 550091.15788602
#Sta/Elev= 30
       0 2826.72    19.3 2821.57    26.4 2820.33    31.1 2819.78    76.9 2817.76
   104.7 2816.93   112.9 2816.91     151 2815.98   157.6 2816.03   201.7    2815
   212.2 2815.11   234.7 2814.84   238.8 2814.07   242.2 2813.22   247.1 2811.59
   252.12810.293   255.3 2809.09   259.4  2808.4   263.5 2809.37   265.42810.721
   271.8 2815.58   275.9 2816.16   279.7 2816.23   288.3 2816.02   292.4 2816.18
   296.5 2816.69   308.9 2817.29   312.6 2817.76   321.3 2818.42   352.2    2819
#Mann= 4 ,-1,0
       0     .06       0      80     .08       0   252.1    .045       0
   265.4     .08       0
Bank Sta=252.1,265.4
XS Rating Curve= 0 ,0
Exp/Cntr(USF)=0,0
Exp/Cntr=0.3,0.1

Type RM Length L Ch R = 1 ,24298   ,77.9,74.7,71.4
XS GIS Cut Line= 3
2315299.97223031549843.5361773812315261.62165426549873.370978166
 2315007.1885518549987.549228962
#Sta/Elev= 30
       0 2818.39    12.4 2816.95    18.1 2816.51    43.8 2815.33    73.7 2815.09
      98 2815.17   113.1 2814.33   124.7 2814.23   137.9 2814.48   142.2 2814.28
     151 2813.15   159.8 2811.35   164.5 2811.25   176.6 2808.71   181.7 2807.87
   186.1 2807.79   188.7 2808.98   190.5 2809.97   194.9 2813.53     208 2814.31
   212.4 2814.77   216.8 2814.99   243.2 2814.96   278.2 2814.06   286.9 2814.03
   294.7 2815.18   300.1 2816.58   302.1 2816.79   312.8 2817.35   327.5 2817.47
#Mann= 4 ,-1,0
       0     .08       0   176.6    .045       0   188.7     .08       0
  327.47     .05       0
#XS Ineff= 2 , 0
             140 2815.22  215.74         2815.18
Permanent Ineff=
       F       F
Bank Sta=176.6,188.7
XS Rating Curve= 0 ,0
Exp/Cntr(USF)=0,0
Exp/Cntr=0.5,0.3

Type RM Length L Ch R = 1 ,24223   ,46.3,46.2,46.1
XS GIS Cut Line= 2
2315259.65880757549738.5155129272314983.93446414549966.036299819
#Sta/Elev= 30
       0 2823.25    35.6 2818.85    40.8 2818.03    54.5 2816.63      67 2815.62
    95.3 2814.03   112.3 2813.56   123.6 2813.38   136.2 2813.54   149.3 2813.31
   170.5 2813.47   173.9 2812.89   175.7 2812.34   180.8 2809.14   183.4 2808.21
     186 2807.57   191.9  2807.8   194.7 2808.85     199 2812.06   200.4 2812.85
   201.6 2813.26   232.7 2812.56   274.2 2812.53     280 2812.76   294.9 2813.22
   305.6 2813.93   312.1 2814.77   318.4 2815.84     326 2816.53   357.5 2817.42
#Mann= 8 ,-1,0
       0     .06       0      70     .05       0     130     .08       0
   180.8    .045       0   194.7     .08       0     200     .05       0
     280     .08       0     330     .05       0
#XS Ineff= 2 , 0
          170.05  2815.5  204.83          2815.5
Permanent Ineff=
       F       F
Bank Sta=180.8,194.7
XS Rating Curve= 0 ,0
Exp/Cntr(USF)=0,0
Exp/Cntr=0.5,0.3

Type RM Length L Ch R = 1 ,24177   ,86.3,86,85.8
XS GIS Cut Line= 2
2315261.58694984549674.8868182872314956.94047247549930.365667976
#Sta/Elev= 30
       0 2827.57     7.1 2826.78    12.3 2825.15      16 2824.55    33.2 2822.45
    39.5 2821.85      54 2820.99    69.7  2819.3   116.2 2815.74   132.4 2813.86
   140.5 2813.23   171.6  2812.5   192.9 2812.69     209 2812.39   210.7  2812.1
   218.4 2808.43   220.3 2808.03   231.5 2807.36   233.9 2807.47   236.8 2807.98
   240.1  2809.3   246.3 2812.41   249.6 2813.56   252.4 2814.24   299.4 2813.36
   329.1 2813.68   339.7  2814.1   354.7 2815.21   374.6 2816.22   397.6 2816.76
#Mann= 4 ,-1,0
       0     .06       0      80     .05       0   220.3    .045       0
   236.8     .05       0
#XS Ineff= 2 , 0
          214.49  2815.5  243.09          2815.5
Permanent Ineff=
       F       F
Bank Sta=220.3,236.8
XS Rating Curve= 0 ,0
Exp/Cntr(USF)=0,0
Exp/Cntr=0.5,0.3

Type RM Length L Ch R = 1 ,24091   ,154.2,153.3,152.6
XS GIS Cut Line= 2
2315194.74671038549613.1817058532314891.13371727549878.140266972
#Sta/Elev= 30
       0  2822.2    18.8 2820.02    30.2 2819.06    55.7 2816.35    68.5 2815.47
    89.7 2814.47   109.5 2813.13   121.7  2812.8   149.2 2812.71   170.3 2811.67
   188.6 2812.12   194.7 2811.84   200.8 2811.38   205.2 2810.67   210.5  2808.6
   212.9  2807.9   215.8  2807.4   221.1 2807.08   225.8 2807.31   229.6  2808.3
   234.3 2809.43     240 2810.41   248.5 2811.15   279.8 2812.38     322 2813.27
   348.5 2814.29   371.1 2815.86   380.4 2816.71   396.3 2818.61     403 2820.19
#Mann= 3 ,-1,0
       0     .05       0   212.9    .045       0   229.6     .05       0
#XS Ineff= 2 , 0
          148.09 2816.76
Permanent Ineff=
       F       F
Bank Sta=212.9,229.6
XS Rating Curve= 0 ,0
Exp/Cntr(USF)=0,0
Exp/Cntr=0.3,0.1

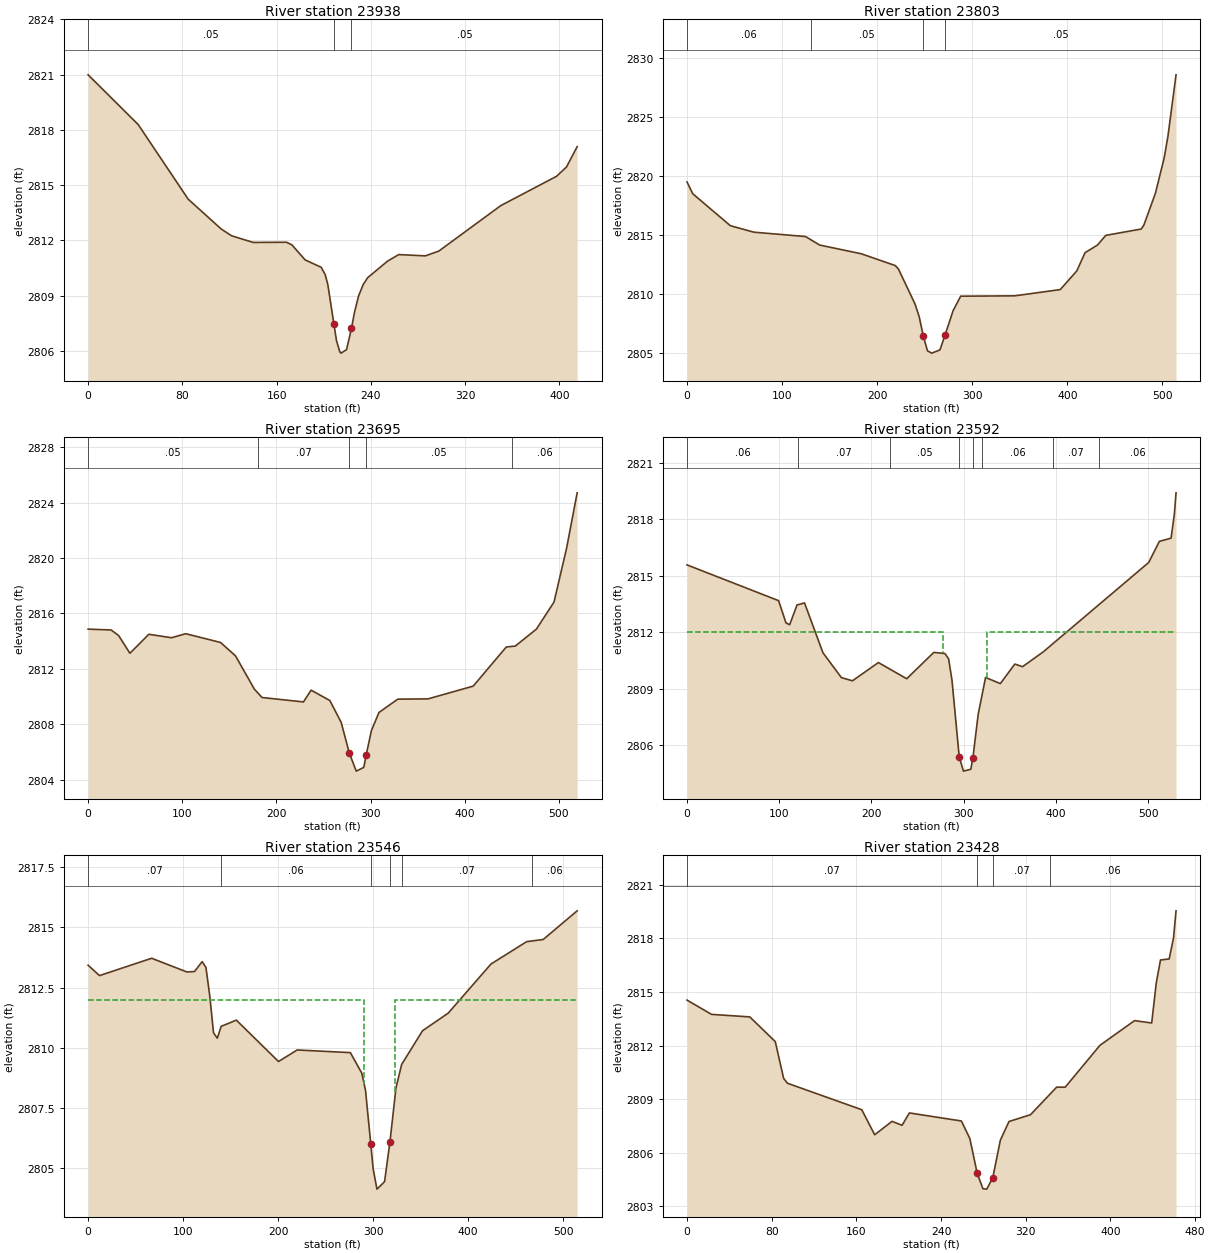
Type RM Length L Ch R = 1 ,23938   ,138.6,134.3,126.4
XS GIS Cut Line= 2
2315084.35258922549487.2262069182314790.25138373549780.018180006
#Sta/Elev= 30
       0 2820.99    42.5 2818.29    84.9 2814.24   113.1 2812.61   121.8 2812.25
   140.1 2811.89   168.4  2811.9   172.9 2811.76   184.2 2810.94   197.8 2810.54
   201.2 2810.14   203.4 2809.61   208.52807.488   210.8 2806.55   213.6 2805.95
   214.7 2805.88   219.3 2806.07   223.52807.221     226 2808.08   229.5 2808.98
   233.4  2809.6   237.3 2809.98   254.2 2810.88   263.6 2811.23   286.2 2811.16
   297.6 2811.42   350.2 2813.89   397.5 2815.48     406 2815.99     415 2817.09
#Mann= 3 ,-1,0
       0     .05       0   208.5    .045       0   223.5     .05       0
Bank Sta=208.5,223.5
XS Rating Curve= 0 ,0
Exp/Cntr(USF)=0,0
Exp/Cntr=0.3,0.1

Type RM Length L Ch R = 1 ,23803   ,111.8,107.8,100.7
XS GIS Cut Line= 2
2314940.20253876549309.1674645212314735.43669572549780.931906832
#Sta/Elev= 30
       0 2819.51     6.1 2818.51    45.6  2815.8    70.4 2815.25   124.7 2814.88
   139.5 2814.16   183.2 2813.42     219 2812.42   222.4 2812.12   239.8 2809.16
   244.2 2808.07   248.6 2806.41   252.9 2805.19   257.3 2804.99     266 2805.26
   271.3  2806.5   279.8 2808.58   287.8 2809.82   344.5 2809.85   392.5 2810.38
   409.9 2811.96   418.6 2813.51   431.7 2814.16   440.4 2814.98   477.7 2815.52
   480.5 2815.86   492.6 2818.55   501.8 2821.54   505.8  2823.4   514.3  2828.6
#Mann= 4 ,-1,0
       0     .06       0     130     .05       0   248.6    .045       0
   271.3     .05       0
Bank Sta=248.6,271.3
XS Rating Curve= 0 ,0
Exp/Cntr(USF)=0,0
Exp/Cntr=0.3,0.1

Type RM Length L Ch R = 1 ,23695   ,104.3,103.8,104.8
XS GIS Cut Line= 3
2314749.37441559549244.8319039762314724.78976373549664.316419729
2314676.63928226549751.068431971
#Sta/Elev= 30
       0 2814.87    24.4 2814.81    32.4 2814.41    44.4 2813.13    64.5  2814.5
    88.5 2814.25   103.7 2814.54   140.6 2813.91   156.6 2812.94   176.6 2810.54
   184.7 2809.94   228.7 2809.62   236.8 2810.47   256.8 2809.72   268.8 2808.14
   277.42805.932   284.8 2804.63   292.8  2804.9   295.32805.779   300.9 2807.56
   308.9 2808.86   328.9 2809.82     361 2809.84     409 2810.76   444.1 2813.58
   453.7 2813.65   476.1 2814.87   494.8 2816.82   508.1 2820.68   519.4  2824.7
#Mann= 5 ,-1,0
       0     .05       0     180     .07       0   277.4    .045       0
   295.3     .05       0   450.2     .06       0
Bank Sta=277.4,295.3
XS Rating Curve= 0 ,0
Exp/Cntr(USF)=0,0
Exp/Cntr=0.5,0.3

Type RM Length L Ch R = 1 ,23592   ,46,45.2,44.2
XS GIS Cut Line= 3
2314649.16299054 549206.056672152314626.45993379549582.322829445
2314503.86675921549674.231037118
#Sta/Elev= 30
       0 2815.58    99.3 2813.68   107.3  2812.5   111.3  2812.4   119.3 2813.45
   127.4 2813.56   147.4 2810.91   167.4 2809.59   179.4 2809.42   207.5 2810.39
   238.2 2809.53   267.6 2810.93   279.6 2810.87   283.6 2810.59   287.3 2809.45
   295.1 2805.39   299.7 2804.62   307.7 2804.72     310 2805.34   315.7 2807.64
   323.7  2809.6   339.7 2809.27   355.4 2810.31   363.8 2810.17   386.3 2810.96
   500.6 2815.71   512.1 2816.83   524.8    2817   528.4 2818.28   530.2 2819.41
#Mann= 8 ,-1,0
       0     .06       0     120     .07       0     220     .05       0
   295.1    .045       0     310     .05       0     320     .06       0
  396.95     .07       0  446.95     .06       0
#XS Ineff= 2 , 0
           277.1    2812  325.22            2812
Permanent Ineff=
       F       F
Bank Sta=295.1,310
XS Rating Curve= 0 ,0
Exp/Cntr(USF)=0,0
Exp/Cntr=0.5,0.3

Type RM Length L Ch R = 1 ,23546   ,115.5,118.8,121.7
XS GIS Cut Line= 3
2314592.38991283549193.2023904052314585.21293885549570.796916674
2314475.63018697549653.064319844
#Sta/Elev= 30
       0 2813.43      12    2813    66.9 2813.72     104 2813.15     112 2813.17
     120 2813.58     124 2813.34     128 2812.17     132 2810.62     136  2810.4
     140 2810.89     156 2811.15   200.4 2809.43     220 2809.91     276  2809.8
     288 2808.95     292 2808.22   297.5    2806     300 2804.97     304 2804.13
     312 2804.44   317.72806.102     324 2808.33     330 2809.31     352 2810.71
     379 2811.44     424 2813.48   461.6 2814.41     479  2814.5   514.7 2815.69
#Mann= 6 ,-1,0
       0     .07       0     140     .06       0   297.5    .045       0
   317.7     .06       0     330     .07       0  467.66     .06       0
#XS Ineff= 2 , 0
          290.43    2812  323.48            2812
Permanent Ineff=
       F       F
Bank Sta=297.5,317.7
XS Rating Curve= 0 ,0
Exp/Cntr(USF)=0,0
Exp/Cntr=0.5,0.3

Type RM Length L Ch R = 1 ,23428   ,239.4,236,232.8
XS GIS Cut Line= 3
2314504.19089341549190.0821854312314512.52237232549282.918664702
2314435.15863959549643.552680335
#Sta/Elev= 30
       0 2814.54    23.2 2813.74    59.3  2813.6    83.4 2812.22    91.3 2810.16
    94.9 2809.89   165.1 2808.41   177.3 2807.01   193.7 2807.76   203.2 2807.54
   210.1 2808.23   259.2 2807.78   267.2  2806.8   274.22804.845   279.6 2803.99
   283.2 2803.97   288.92804.613     296  2806.7   304.2 2807.75   324.5 2808.13
   349.2 2809.67   357.3 2809.67   390.1 2812.01   422.8 2813.39     439 2813.26
   443.3 2815.49   447.3 2816.78   455.5 2816.84   459.6 2818.01     462 2819.53
#Mann= 4 ,-1,0
       0     .07       0   274.2    .045       0   288.9     .07       0
  343.21     .06       0
Bank Sta=274.2,288.9
XS Rating Curve= 0 ,0
Exp/Cntr(USF)=0,0
Exp/Cntr=0.3,0.1

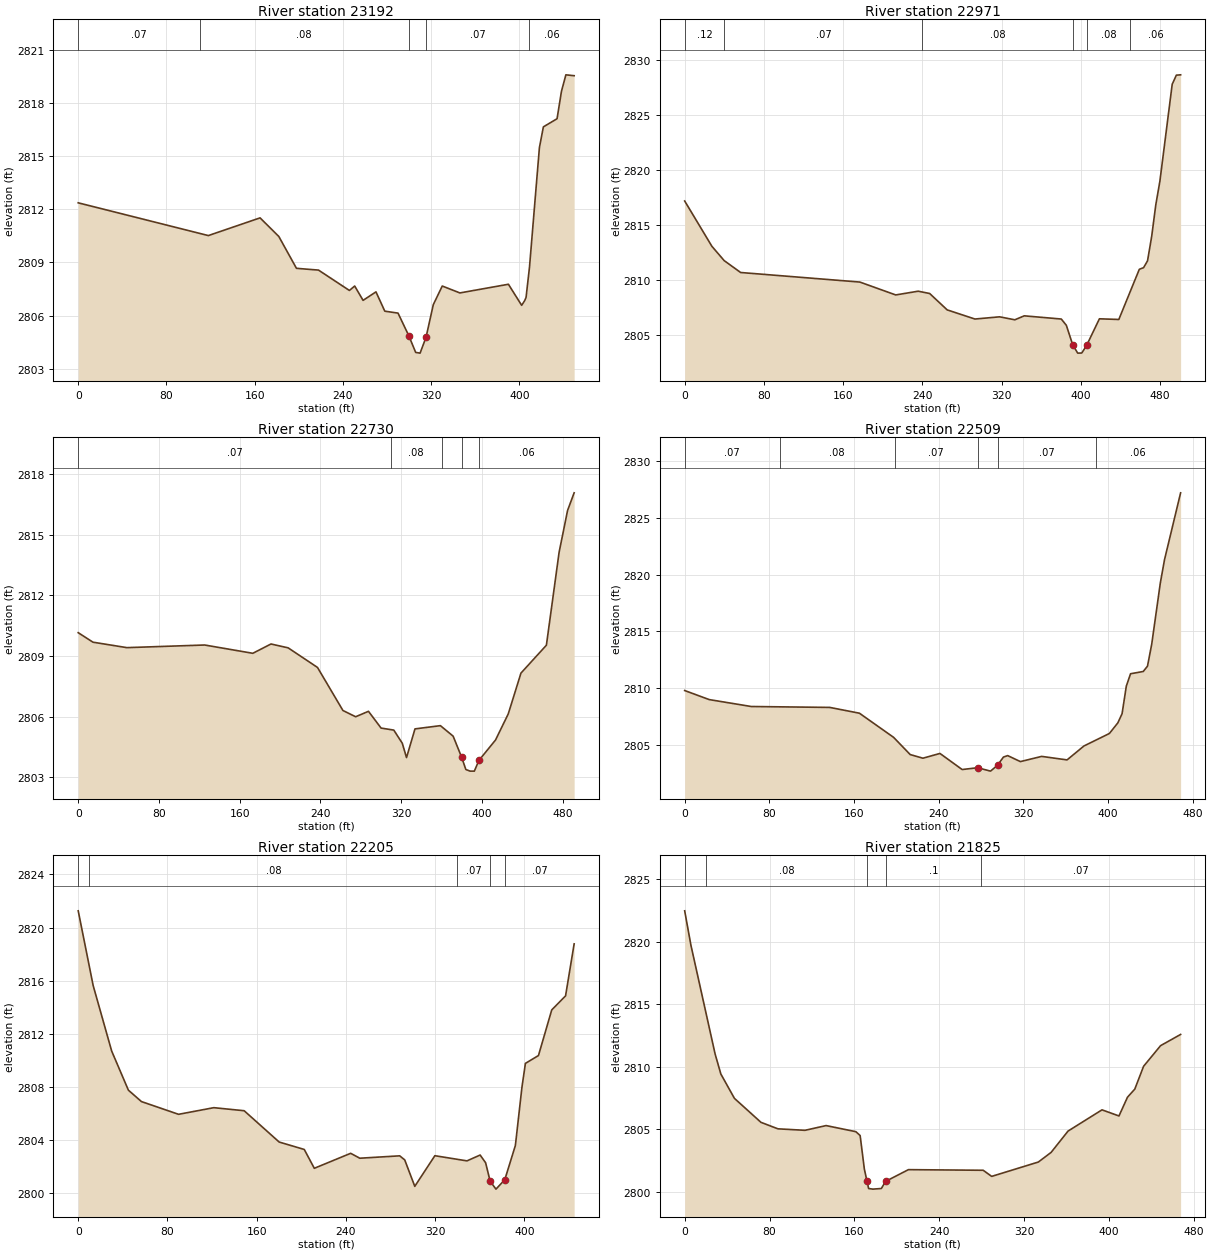
Type RM Length L Ch R = 1 ,23192   ,221.2,221,215.3
XS GIS Cut Line= 3
2314282.35839068549126.0334784572314241.45175496549248.259712441
2314257.17087524549568.687597807
#Sta/Elev= 30
       0 2812.37     118 2810.52   164.9 2811.52   181.9 2810.47   197.9 2808.67
   217.9 2808.57   245.9 2807.42   250.7 2807.67   258.3 2806.86     270 2807.34
     278 2806.25     290 2806.14   299.72804.872     306 2803.92     310 2803.88
   315.42804.775     322 2806.62   330.1 2807.67   346.1 2807.28   390.1 2807.77
   402.1 2806.58   404.9 2806.85   406.1 2807.03   409.2 2808.73   418.2 2815.49
   421.8 2816.66   434.2 2817.12   438.2 2818.67   442.2  2819.6   449.7 2819.55
#Mann= 5 ,-1,0
       0     .07       0     110     .08       0   299.7    .045       0
   315.4     .07       0  408.89     .06       0
Bank Sta=299.7,315.4
XS Rating Curve= 0 ,0
Exp/Cntr(USF)=0,0
Exp/Cntr=0.3,0.1

Type RM Length L Ch R = 1 ,22971   ,240,241,238.4
XS GIS Cut Line= 2
 2314016.4731271549094.6925707332314150.04128104549577.389364667
#Sta/Elev= 30
       0 2817.16    27.5 2813.04    39.9 2811.74    56.5 2810.66   176.9 2809.79
   213.1 2808.62   235.8 2808.96   247.4 2808.75   265.1 2807.26   293.1 2806.43
     318 2806.63   333.4 2806.36   342.9 2806.72   380.3 2806.43   385.4 2805.86
   391.9 2804.07   396.9 2803.33     401 2803.34   405.92804.035   418.8 2806.45
   438.4 2806.39   459.1 2810.95   463.4  2811.1   467.4 2811.72   471.6 2813.95
   475.7 2816.79   479.9 2818.98   492.3 2827.77   496.5  2828.6   500.8 2828.63
#Mann= 6 ,-1,0
       0     .12       0      40     .07       0     240     .08       0
   391.9    .045       0   405.9     .08       0     450     .06       0
Bank Sta=391.9,405.9
XS Rating Curve= 0 ,0
Exp/Cntr(USF)=0,0
Exp/Cntr=0.3,0.1

Type RM Length L Ch R = 1 ,22730   ,217.5,220.7,224.5
XS GIS Cut Line= 2
2313832.65160831549187.2645586112313982.08924589549655.414325879
#Sta/Elev= 30
       0 2810.16    14.6 2809.69    48.2 2809.42   125.3 2809.55     173 2809.14
     191  2809.6     208 2809.41   237.1 2808.44   262.3 2806.31   274.9    2806
   287.6 2806.27   300.1 2805.44   312.7 2805.34   321.1 2804.69   325.3 2803.98
   333.7  2805.4   358.9 2805.56   371.5 2805.04   379.9    2804   384.1 2803.39
   388.3 2803.31   392.5 2803.31   397.12803.844   413.5 2804.85   426.1 2806.14
   438.7 2808.16   463.9 2809.54   476.5 2814.14   484.9 2816.21   491.4 2817.08
#Mann= 5 ,-1,0
       0     .07       0     310     .08       0     360     .06       0
   379.9    .045       0   397.1     .06       0
Bank Sta=379.9,397.1
XS Rating Curve= 0 ,0
Exp/Cntr(USF)=0,0
Exp/Cntr=0.3,0.1

Type RM Length L Ch R = 1 ,22509   ,303.4,304.2,295.2
XS GIS Cut Line= 3
2313679.24659983549244.1302083072313733.46733559549360.506421639
2313748.01436225549700.377862848
#Sta/Elev= 30
       0 2809.77    23.2 2808.97    62.9 2808.36   137.1 2808.28   165.1 2807.77
   197.4 2805.64   213.1 2804.12   225.1  2803.8   241.2 2804.22   262.2  2802.8
   276.8 2802.96     289 2802.66   295.6 2803.18   301.2  2803.9   305.2 2804.03
   317.2  2803.5   337.3 2803.96   361.3 2803.65   377.3 2804.88   401.3 2805.98
   409.3 2806.92   413.3 2807.73   417.3 2810.16   421.3 2811.25   433.3 2811.45
   437.3 2811.92   441.3 2813.86   449.4 2819.24   453.4 2821.32   468.6 2827.21
#Mann= 6 ,-1,0
       0     .07       0      90     .08       0  198.39     .07       0
   276.8    .045       0   295.6     .07       0  388.39     .06       0
Bank Sta=276.8,295.6
XS Rating Curve= 0 ,0
Exp/Cntr(USF)=0,0
Exp/Cntr=0.3,0.1

Type RM Length L Ch R = 1 ,22205   ,359.3,379.5,371.7
XS GIS Cut Line= 2
2313407.68297051549321.2519314082313612.45167871549716.039059512
#Sta/Elev= 30
       0 2821.26    13.4 2815.63      30 2810.69      45 2807.74    56.7 2806.88
      90 2805.92   121.6 2806.42   148.8 2806.19   180.2 2803.83   202.7 2803.27
   211.7 2801.85   244.3 2802.98   252.5 2802.61   288.3 2802.79   292.8 2802.48
   301.8 2800.49   319.8  2802.8   348.6 2802.41   360.4 2802.85   365.3 2802.27
   369.4 2800.87   374.6 2800.28   382.5 2800.99     392 2803.57   397.9 2807.97
     401 2809.76   412.7 2810.35   424.6 2813.79     437 2814.85   444.7 2818.77
#Mann= 5 ,-1,0
       0      .1       0      10     .08       0     340     .07       0
   369.4    .045       0   382.5     .07       0
Bank Sta=369.4,382.5
XS Rating Curve= 0 ,0
Exp/Cntr(USF)=0,0
Exp/Cntr=0.3,0.1

Type RM Length L Ch R = 1 ,21825   ,300.9,310.1,301.1
XS GIS Cut Line= 4
2313327.85788087549355.9584921212313375.57940185549443.592557919
2313381.65304998 549768.098900582313414.62428265 549795.86414915
#Sta/Elev= 30
       0 2822.48     5.9 2819.72    28.7 2811.01    34.1 2809.41    46.9 2807.46
    71.9 2805.54    87.9 2805.02   113.4  2804.9   133.3 2805.28   161.4 2804.79
   165.4 2804.48   169.4 2801.78   171.92800.811   173.4 2800.24   177.4 2800.19
   185.4 2800.24   189.4 2800.81   210.9 2801.75   281.4  2801.7   289.4 2801.21
   333.4 2802.36   345.4 2803.13   361.4 2804.84   393.4 2806.54   409.4 2806.05
   417.4 2807.55   424.3  2808.2   432.6 2810.03   448.6 2811.68   467.5 2812.58
#Mann= 5 ,-1,0
       0      .1       0      20     .08       0   171.9    .045       0
   189.4      .1       0  279.79     .07       0
Bank Sta=171.9,189.4
XS Rating Curve= 0 ,0
Exp/Cntr(USF)=0,0
Exp/Cntr=0.3,0.1