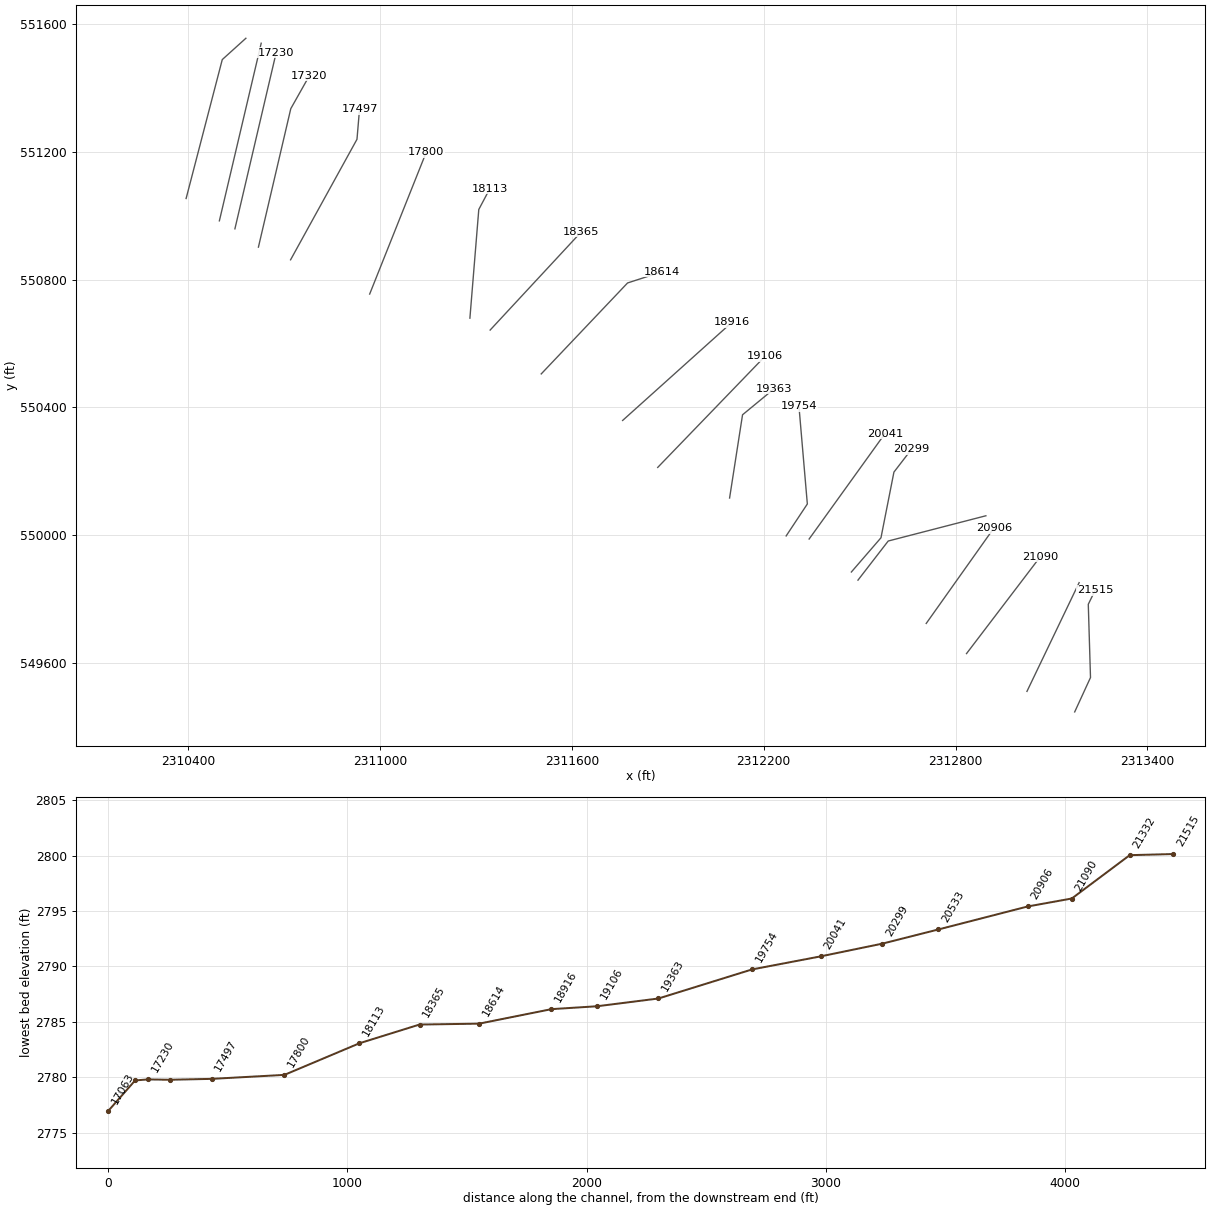
HEC-RAS study BRSHRN.prj: BRSHRN

--- BRSHRN.g01 (geometry) --- (continued)

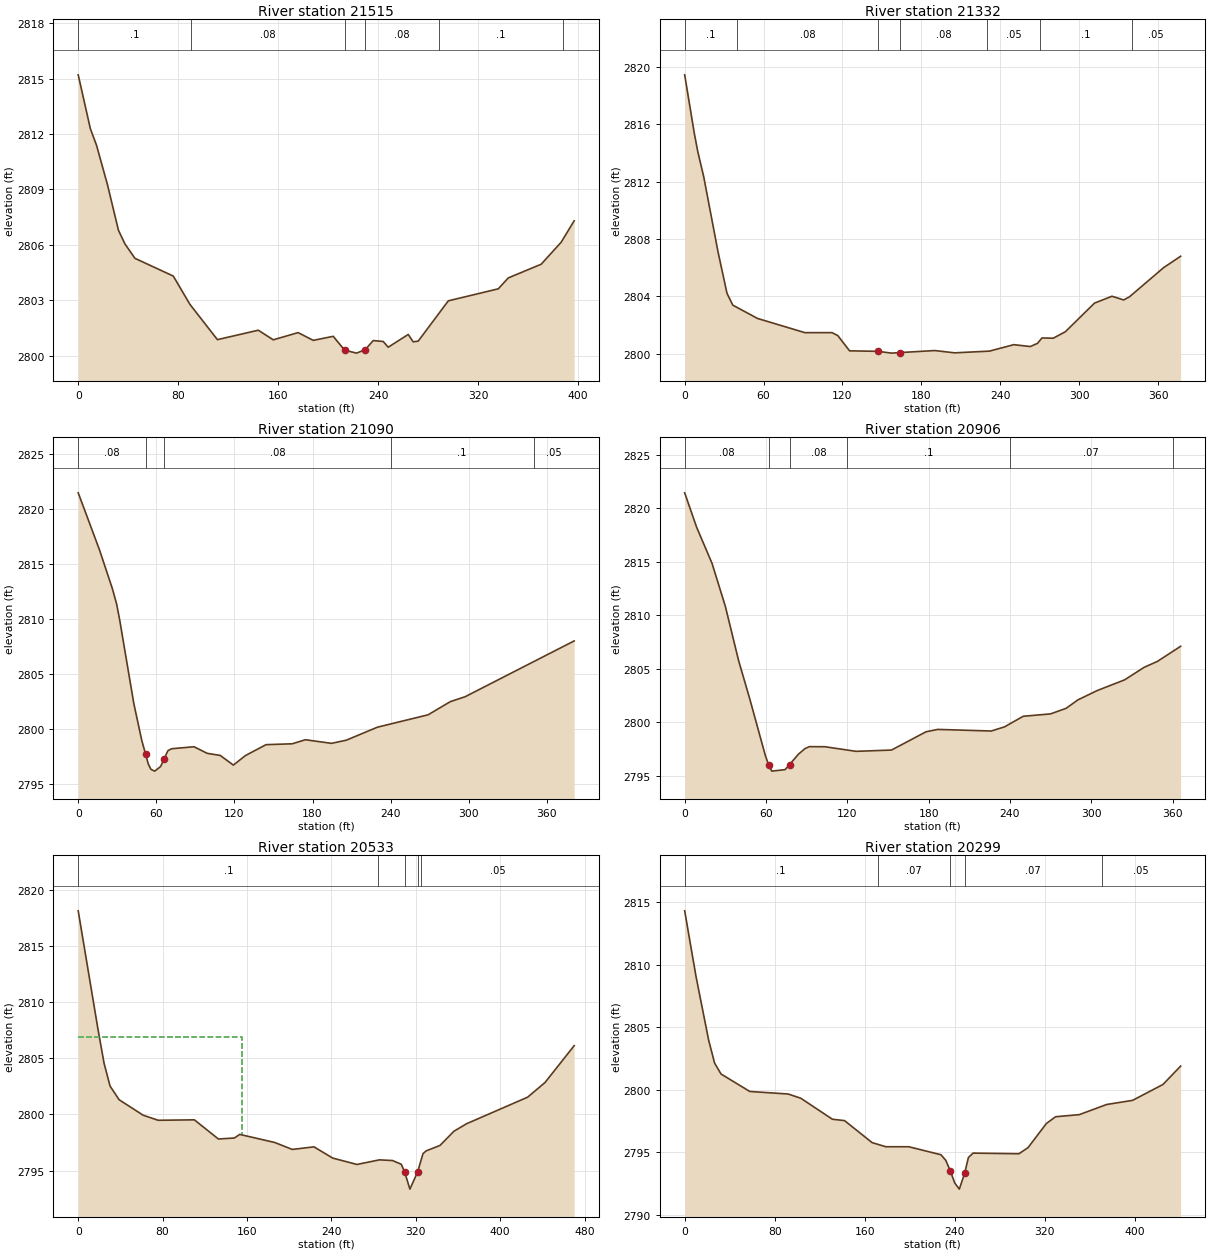
Type RM Length L Ch R = 1 ,21515   ,181.8,182.7,172
XS GIS Cut Line= 4
2313172.54602168549447.930878008 2313222.0028707549555.521216217
2313215.06155856549784.584516918  2313236.753159549828.835381827
#Sta/Elev= 30
       0  2815.2     9.7 2812.29    14.6  2811.4    23.4 2809.26    32.2 2806.79
    37.4 2806.05    45.4 2805.27    76.1 2804.31    89.4 2802.78   111.4 2800.87
   144.1 2801.38   156.1 2800.86     176 2801.25   188.1 2800.83   204.1 2801.05
   213.2  2800.3   222.8 2800.14   229.7 2800.33   236.1 2800.82   244.1 2800.77
   248.1 2800.46   264.1 2801.15   268.1 2800.75   272.1 2800.79   296.2 2802.97
   336.2 2803.62   344.2 2804.21   370.5 2804.95   386.5 2806.14   396.9  2807.3
#Mann= 6 ,-1,0
       0      .1       0      90     .08       0   213.2    .045       0
   229.7     .08       0  288.41      .1       0  387.58     .05       0
Bank Sta=213.2,229.7
XS Rating Curve= 0 ,0
Exp/Cntr(USF)=0,0
Exp/Cntr=0.3,0.1

Type RM Length L Ch R = 1 ,21332   ,243.6,242,241.4
XS GIS Cut Line= 2
2313023.30781062549512.1380153262313186.42864597549852.262310307
#Sta/Elev= 30
       0 2819.46     7.4 2815.34      10 2814.09    14.5 2812.34    25.4 2807.09
    32.2 2804.21    36.6 2803.39    55.4 2802.46    91.4 2801.47   112.1 2801.47
   116.5 2801.26   125.4  2800.2   147.12800.165   157.3 2800.04     164 2800.08
   190.3 2800.22   205.3 2800.06   231.8 2800.18   250.3 2800.63   262.9  2800.5
   268.3 2800.72   271.8  2801.1   280.3 2801.08   289.5 2801.53   311.7 2803.53
     325 2804.01   333.9 2803.75   338.3 2803.97   364.2    2806   377.2  2806.8
#Mann= 7 ,-1,0
       0      .1       0      40     .08       0   147.1    .045       0
     164     .08       0     230     .05       0     270      .1       0
     340     .05       0
Bank Sta=147.1,164
XS Rating Curve= 0 ,0
Exp/Cntr(USF)=0,0
Exp/Cntr=0.3,0.1

Type RM Length L Ch R = 1 ,21090   ,180.7,184.5,184
XS GIS Cut Line= 2
2312834.32636862549630.3687869462313065.18981911549933.502534984
#Sta/Elev= 30
       0 2821.48    16.3  2816.3    26.2 2812.77    29.5 2811.36    31.9 2809.88
    42.7  2802.3    48.8 2798.94    51.8 2797.66    53.8 2796.79    55.9 2796.29
    58.8 2796.13    63.3 2796.55    66.1 2797.28    68.9 2797.99    71.8 2798.17
      89 2798.35    99.1 2797.75   109.1 2797.56   119.2 2796.68   128.5 2797.55
   144.3 2798.54   164.4 2798.62   174.5 2798.99   194.6 2798.66     206 2798.95
   229.8 2800.13   268.8 2801.26   285.9 2802.46   297.3 2802.91     381 2807.99
#Mann= 5 ,-1,0
       0     .08       0    51.8    .045       0    66.1     .08       0
     240      .1       0     350     .05       0
Bank Sta=51.8,66.1
XS Rating Curve= 0 ,0
Exp/Cntr(USF)=0,0
Exp/Cntr=0.3,0.1

Type RM Length L Ch R = 1 ,20906   ,380.7,372.6,361.5
XS GIS Cut Line= 2
2312708.34577216549724.715699689 2312920.0557925550023.192121816
#Sta/Elev= 30
       0 2821.43     8.8 2818.22    20.2 2814.83      30 2810.82    39.8 2805.74
    48.1 2802.13    59.4 2796.92    61.9 2795.99    64.3 2795.41    74.1 2795.55
    77.42796.025    83.9 2796.99    88.8 2797.52      92  2797.7   103.6 2797.69
   126.4 2797.26   152.6 2797.38   178.1 2799.09   186.7 2799.31   226.2 2799.16
     236 2799.55   249.8 2800.54   269.9 2800.76   281.4 2801.28   290.1 2802.07
   304.3 2802.94   324.7 2803.95   338.9 2805.11   348.8 2805.67   365.9 2807.08
#Mann= 6 ,-1,0
       0     .08       0    61.9    .045       0    77.4     .08       0
     120      .1       0     240     .07       0     360     .05       0
Bank Sta=61.9,77.4
XS Rating Curve= 0 ,0
Exp/Cntr(USF)=0,0
Exp/Cntr=0.3,0.1

Type RM Length L Ch R = 1 ,20533   ,220.5,234.2,245.3
XS GIS Cut Line= 3
2312494.90042378549860.0712864682312589.47580172549982.411912979
2312894.89353599  550061.3693386
#Sta/Elev= 30
       0 2818.16    18.8 2807.57    24.5 2804.57    30.2 2802.53    38.8 2801.31
    61.6 2799.93    75.8 2799.48   110.1 2799.52   132.9 2797.81     148  2797.9
   153.1 2798.22   186.3  2797.5   202.9 2796.88   223.5 2797.11   241.2 2796.11
   264.2 2795.54   285.5 2795.95   297.9 2795.89   306.2 2795.56   309.42794.889
   314.4 2793.34   321.72794.865   326.8  2796.5   329.8 2796.75     343 2797.24
   356.1  2798.5   368.1 2799.17     426 2801.54   442.5 2802.85   470.1 2806.13
#Mann= 5 ,-1,0
       0      .1       0  284.63     .07       0   309.4    .045       0
   321.7     .07       0  324.63     .05       0
#XS Ineff= 2 , 0
          155.07 2806.89
Permanent Ineff=
       F       F
Bank Sta=309.4,321.7
XS Rating Curve= 0 ,0
Exp/Cntr(USF)=0,0
Exp/Cntr=0.3,0.1

Type RM Length L Ch R = 1 ,20299   ,261.6,258.1,251.6
XS GIS Cut Line= 4
2312474.26930157549885.5227643242312566.82013014549992.534659853
2312607.31111764550197.881810735 2312662.2631721550269.223074422
#Sta/Elev= 30
       0 2814.32    10.1 2809.06    21.3 2803.98    26.6 2802.14    32.3 2801.27
    57.9 2799.87    91.9 2799.67   103.2 2799.33   131.3 2797.65   142.1 2797.54
   166.6 2795.78   178.8 2795.45   199.2 2795.45   227.8 2794.81     232 2794.37
     2362793.543     240 2792.56   244.1 2792.06   248.8 2793.32   252.2 2794.59
   256.3 2794.94   297.1 2794.89   305.2 2795.38   321.5 2797.31   329.7 2797.85
   350.8 2798.02   375.1 2798.83   398.1 2799.16   425.1 2800.43   440.8  2801.9
#Mann= 5 ,-1,0
       0      .1       0  171.48     .07       0     236    .045       0
   248.8     .07       0  370.78     .05       0
Bank Sta=236,248.8
XS Rating Curve= 0 ,0
Exp/Cntr(USF)=0,0
Exp/Cntr=0.3,0.1

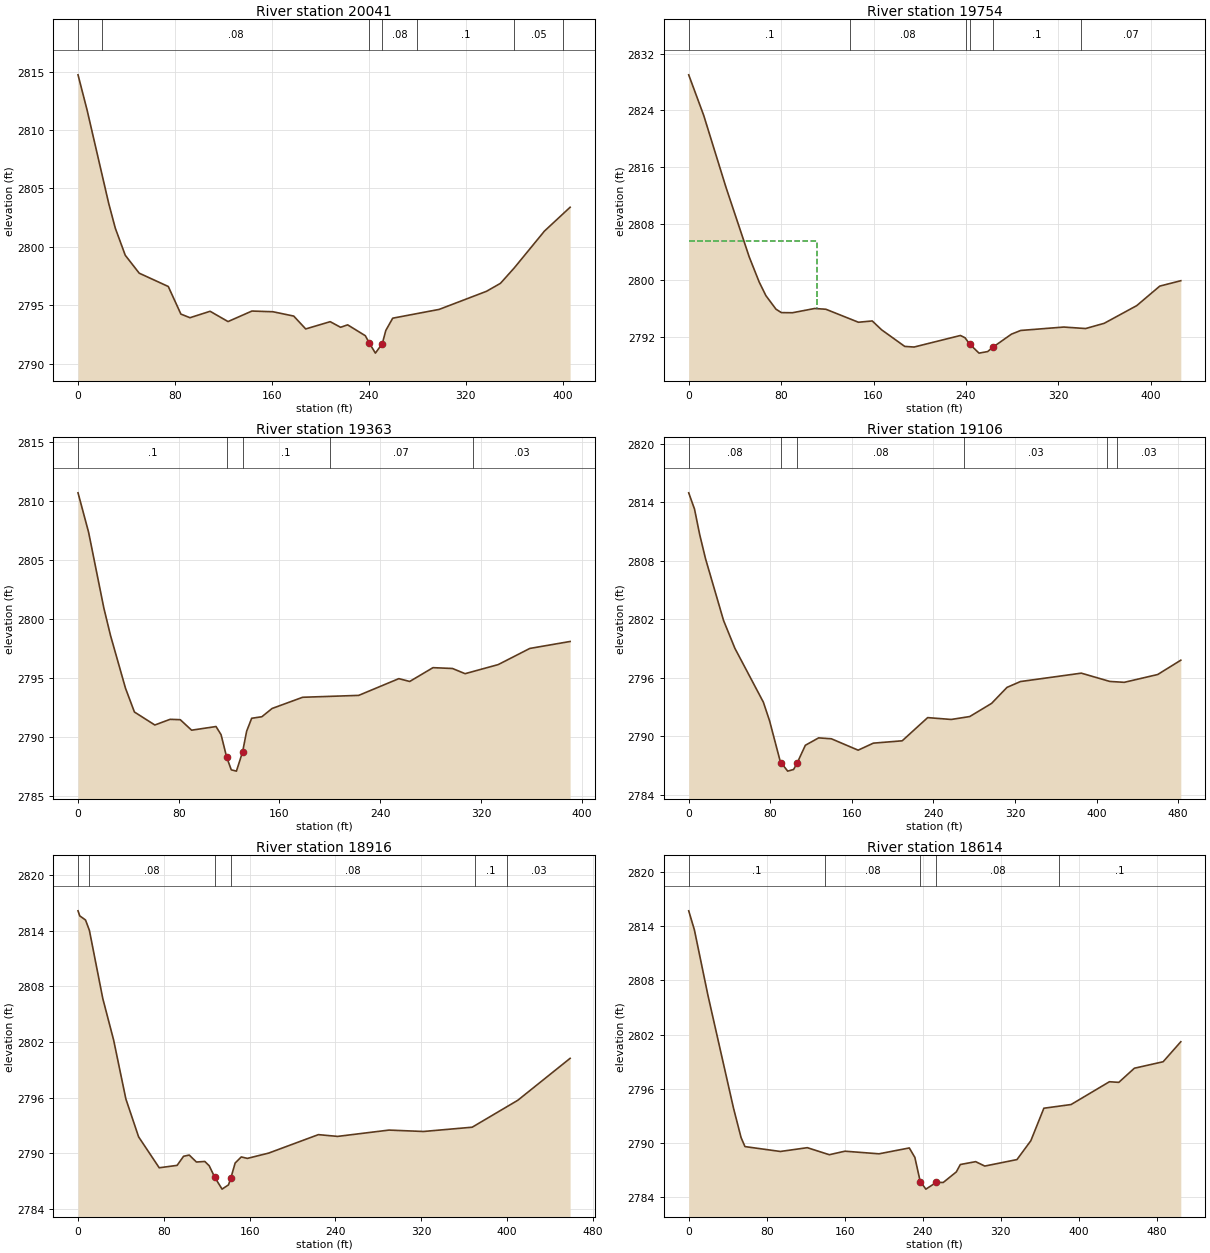
Type RM Length L Ch R = 1 ,20041   ,274.3,287,294.7
XS GIS Cut Line= 2
2312342.19155664 549988.678375332312579.35305484550318.390702097
#Sta/Elev= 30
       0 2814.72     7.5  2811.7    25.3 2803.73    30.8 2801.59      39 2799.28
    50.5 2797.75    74.5 2796.61    84.9 2794.25    92.4 2793.94     109 2794.49
   123.8 2793.61   143.5 2794.51   160.9 2794.45     178 2794.08   187.9 2792.98
   208.1  2793.6   216.7 2793.12   222.5 2793.33   237.1  2792.4   240.42791.771
   245.4 2790.91   251.1 2791.72     254 2792.85   259.7  2793.9     298 2794.65
   337.1  2796.2   348.6 2796.88     360  2798.2   384.9 2801.35   406.1 2803.39
#Mann= 7 ,-1,0
       0      .1       0      20     .08       0   240.4    .045       0
   251.1     .08       0     280      .1       0     360     .05       0
     400      .1       0
Bank Sta=240.4,251.1
XS Rating Curve= 0 ,0
Exp/Cntr(USF)=0,0
Exp/Cntr=0.3,0.1

Type RM Length L Ch R = 1 ,19754   ,388.4,390.9,371.6
XS GIS Cut Line= 3
2312270.36241784 549998.342444822312336.56586186550098.209012417
2312310.37720932550403.228961616
#Sta/Elev= 30
       0 2829.01      13 2823.28    32.2 2813.17    52.4  2803.3      61 2799.77
    66.8 2797.85    75.5 2795.94    80.2 2795.45    89.8 2795.43     109 2796.03
   118.8 2795.92   146.9 2794.09   158.9 2794.27     167 2793.02     187 2790.68
   195.1 2790.59   235.2 2792.22   239.2  2791.9   243.2 2791.01   251.3 2789.73
   258.8 2789.95   263.2 2790.55   279.4 2792.41   287.4 2792.93   324.7 2793.41
   343.6  2793.2   359.7 2793.94   387.8 2796.43   407.8 2799.19     426 2799.95
#Mann= 6 ,-1,0
       0      .1       0  139.82     .08       0  239.82      .1       0
   243.2    .045       0   263.2      .1       0  339.82     .07       0
#XS Ineff= 2 , 0
          110.94  2805.5
Permanent Ineff=
       F       F
Bank Sta=243.2,263.2
XS Rating Curve= 0 ,0
Exp/Cntr(USF)=0,0
Exp/Cntr=0.3,0.1

Type RM Length L Ch R = 1 ,19363   ,261.3,256.7,248.8
XS GIS Cut Line= 3
2312093.46120487550116.8998357392312133.95219237550377.199041082
2312232.28744772550458.181016078
#Sta/Elev= 30
       0  2810.7     8.4 2807.36    20.5 2800.94    25.8 2798.61    37.7 2794.14
    44.8 2792.12      61 2791.02    73.1  2791.5    81.2 2791.47    90.2 2790.58
   109.6 2790.89   113.6  2790.2     1182788.314   121.7 2787.22   125.8 2787.11
   130.72788.742   133.9 2790.49   137.9 2791.59     146 2791.72   154.1 2792.42
   178.4 2793.37   222.9 2793.53   254.8 2794.95   263.4 2794.71   281.9 2795.88
   297.4 2795.81   307.4 2795.37   333.7 2796.14   358.8 2797.51   390.8  2798.1
#Mann= 5 ,-1,0
       0      .1       0     118    .045       0   130.7      .1       0
     200     .07       0  313.43     .03       0
Bank Sta=118,130.7
XS Rating Curve= 0 ,0
Exp/Cntr(USF)=0,0
Exp/Cntr=0.3,0.1

Type RM Length L Ch R = 1 ,19106   ,192.3,190.2,190.7
XS GIS Cut Line= 2
2311868.71489308 550212.546183842312203.96877336550559.845113712
#Sta/Elev= 30
       0 2814.96     5.7 2813.29    10.7 2810.71    16.5  2808.2    34.2 2801.86
    45.3 2799.01    73.2 2793.49    79.3 2791.58    89.8  2787.4      91 2787.22
    97.1 2786.41   102.9 2786.58   106.5 2787.27   114.4 2789.06   127.4 2789.82
   139.9 2789.73   166.2 2788.56   181.1 2789.28   209.4 2789.52   234.4  2791.9
   257.5 2791.71   275.7 2792.01   297.1 2793.36   312.2    2795   325.4  2795.6
   385.1 2796.46   413.1 2795.61   427.2 2795.52     460 2796.32   482.7 2797.79
#Mann= 6 ,-1,0
       0     .08       0      91    .045       0   106.5     .08       0
     270     .03       0     410     .07       0     420     .03       0
Bank Sta=91,106.5
XS Rating Curve= 0 ,0
Exp/Cntr(USF)=0,0
Exp/Cntr=0.3,0.1

Type RM Length L Ch R = 1 ,18916   ,301.1,302.6,303.4
XS GIS Cut Line= 2
 2311758.9931759550359.4315378152312100.27435624550666.006157441
#Sta/Elev= 30
       0 2816.13     1.6 2815.59       7 2815.14    10.6 2814.03    23.1 2806.68
    33.2 2802.21    44.6 2795.87    56.5 2791.78    75.7 2788.45    92.4 2788.71
    98.4 2789.69   103.7 2789.82   110.4 2789.07   118.2 2789.13   122.3 2788.67
   127.5 2787.42   134.3 2786.15   140.3 2786.61  142.61  2787.4   146.5 2788.96
   152.2 2789.62   157.9 2789.46   177.7 2790.03   224.1 2792.02     242 2791.83
   289.9 2792.51   322.1 2792.36   367.5 2792.82     410 2795.72   458.8 2800.24
#Mann= 6 ,-1,0
       0      .1       0      10     .08       0   127.5    .045       0
  142.61     .08       0     370      .1       0     400     .03       0
Bank Sta=127.5,142.61
XS Rating Curve= 0 ,0
Exp/Cntr(USF)=0,0
Exp/Cntr=0.3,0.1

Type RM Length L Ch R = 1 ,18614   ,246.5,248.9,247.3
XS GIS Cut Line= 3
2311504.47839734550505.0062785812311774.41831399550789.407262196
2311881.43020952550824.113822909
#Sta/Elev= 30
       0 2815.73     5.8 2813.63    19.7 2806.36      46  2793.8    53.7 2790.56
    57.7 2789.56      94 2789.02   121.6 2789.44   144.2 2788.66   160.2 2789.05
   195.1 2788.76   226.2 2789.41   231.9 2788.36   237.4 2785.68   243.2 2784.84
   253.9 2785.59     261 2785.58   274.4 2786.75   278.5 2787.57   294.2 2787.89
   303.6  2787.4   336.6 2788.12   350.8 2790.21   364.2 2793.82   392.1 2794.23
   431.4 2796.76     441 2796.69     457 2798.26   486.5 2798.98   504.6  2801.2
#Mann= 5 ,-1,0
       0      .1       0     140     .08       0   237.4    .045       0
   253.9     .08       0     380      .1       0
Bank Sta=237.4,253.9
XS Rating Curve= 0 ,0
Exp/Cntr(USF)=0,0
Exp/Cntr=0.3,0.1

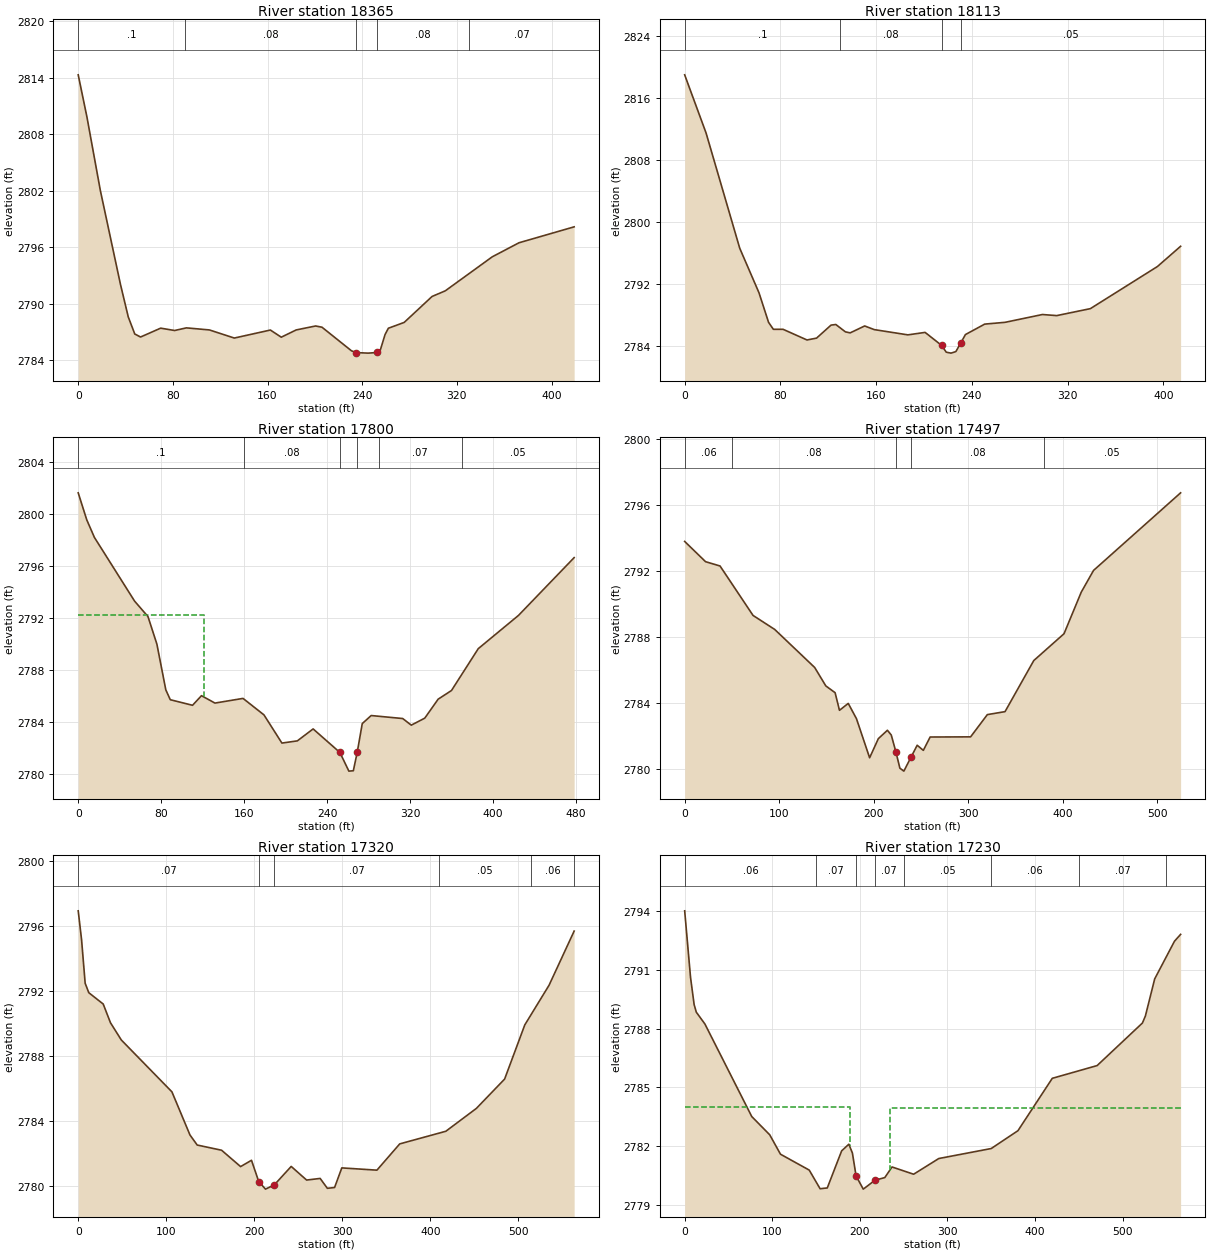
Type RM Length L Ch R = 1 ,18365   ,239.6,251.3,257.7
XS GIS Cut Line= 2
2311344.75523587550642.1529525832311629.82140952550949.301717152
#Sta/Elev= 30
       0 2814.29     7.4  2809.8    18.7 2802.02    35.7 2792.06    42.3  2788.6
    47.8 2786.79    52.7 2786.47    69.7 2787.41    81.5 2787.16    91.4 2787.44
   110.9 2787.22   131.9 2786.36   162.4 2787.21   171.6 2786.45   184.2 2787.22
   200.6 2787.64     206 2787.51     231    2785   235.12784.816   245.1 2784.76
   252.92784.829   255.2 2785.05   259.3 2786.73   262.1  2787.4   275.5 2788.02
     299 2790.77   310.2 2791.37   349.9 2794.98   372.5 2796.47   419.1 2798.16
#Mann= 5 ,-1,0
       0      .1       0      90     .08       0   235.1    .045       0
   252.9     .08       0     330     .07       0
Bank Sta=235.1,252.9
XS Rating Curve= 0 ,0
Exp/Cntr(USF)=0,0
Exp/Cntr=0.3,0.1

Type RM Length L Ch R = 1 ,18113   ,314.3,313.2,303.2
XS GIS Cut Line= 3
2311281.44470695550679.3140419272311309.21630331551019.185483136
2311343.60018452 551083.98587465
#Sta/Elev= 30
       0 2819.04    17.9 2811.51      46 2796.63    62.1 2790.87    70.1 2787.05
    74.1 2786.15    82.2 2786.15   102.2 2784.77   110.2 2785.01   122.3 2786.69
   126.3 2786.77   134.3 2785.82   138.3 2785.69   150.4 2786.58   158.4 2786.11
   186.5 2785.43   200.9 2785.75   214.6 2784.08   218.6 2783.19   222.6 2783.07
   226.6 2783.27   230.7 2784.39   234.6 2785.47   250.7 2786.82   267.7 2787.05
   298.9 2788.06   310.9 2787.92     339 2788.82     395 2794.26   414.4 2796.88
#Mann= 4 ,-1,0
       0      .1       0     130     .08       0   214.6    .045       0
   230.7     .05       0
Bank Sta=214.6,230.7
XS Rating Curve= 0 ,0
Exp/Cntr(USF)=0,0
Exp/Cntr=0.3,0.1

Type RM Length L Ch R = 1 ,17800   ,303.4,303.6,297.7
XS GIS Cut Line= 2
2310968.02240513550754.6940891992311145.23163907551199.039631012
#Sta/Elev= 30
       0 2801.65     8.2 2799.58    15.6 2798.22    54.4 2793.31    67.3 2792.12
    75.9    2790    84.5 2786.48    88.8 2785.72   110.3 2785.29   118.9 2786.03
   131.9 2785.46     159 2785.82   179.2 2784.55   196.5 2782.38   211.4 2782.55
   226.6 2783.47   252.4 2781.66   261.1 2780.22   265.4 2780.25   269.2 2781.69
     274 2783.88   282.6  2784.5     313 2784.27   321.3 2783.76   334.3  2784.3
   347.2 2785.76   360.1 2786.43   385.9 2789.65   424.7 2792.21   478.4 2796.66
#Mann= 6 ,-1,0
       0      .1       0     160     .08       0   252.4    .045       0
   269.2     .08       0     290     .07       0     370     .05       0
#XS Ineff= 2 , 0
          121.26 2792.26
Permanent Ineff=
       F       F
Bank Sta=252.4,269.2
XS Rating Curve= 0 ,0
Exp/Cntr(USF)=0,0
Exp/Cntr=0.3,0.1

Type RM Length L Ch R = 1 ,17497   ,173.2,176.6,179.7
XS GIS Cut Line= 3
 2310720.7229518550861.8131037432310928.34869604551238.713340103
2310936.28343786 551332.60778495
#Sta/Elev= 30
       0  2793.8    22.1 2792.57    37.4 2792.31    72.3 2789.31    95.2 2788.46
   137.5 2786.15   149.3 2785.03   159.1 2784.62   163.7 2783.55     173 2783.97
   181.7 2783.04   195.6 2780.67   204.8 2781.83   214.4 2782.34   218.5 2782.05
   223.5    2781   227.6 2780.04   231.8 2779.86   239.3  2780.7   245.9 2781.43
   252.4 2781.12   259.6 2781.93   302.4 2781.94   320.1 2783.29   338.8 2783.47
   369.2 2786.57   401.2  2788.2   419.4 2790.72   432.4 2792.04   524.5 2796.75
#Mann= 5 ,-1,0
       0     .06       0      50     .08       0   223.5    .045       0
   239.3     .08       0     380     .05       0
Bank Sta=223.5,239.3
XS Rating Curve= 0 ,0
Exp/Cntr(USF)=0,0
Exp/Cntr=0.3,0.1

Type RM Length L Ch R = 1 ,17320   ,90.2,90.5,91.4
XS GIS Cut Line= 3
2310620.16659814550901.4905240212310721.35717034551334.437015738
 2310779.6775227551437.985396464
#Sta/Elev= 30
       0 2796.95     3.8 2795.18     7.9 2792.48      12  2791.9    28.4  2791.2
    36.7 2790.04      49 2788.98   106.5 2785.78     127 2783.12   135.2  2782.5
   162.9 2782.18   184.5 2781.17   196.9 2781.56   205.1 2780.25   212.8 2779.78
   222.8 2780.04     242 2781.18   259.5 2780.34   274.9 2780.44   283.1 2779.83
   291.3 2779.88   299.5 2781.09   339.4 2780.95   365.3 2782.57   417.7 2783.35
   452.4 2784.76   484.5 2786.57   507.4 2789.91     535 2792.36   563.5  2795.7
#Mann= 6 ,-1,0
       0     .07       0   205.1    .045       0   222.8     .07       0
     410     .05       0  514.61     .06       0  563.46     .05       0
Bank Sta=205.1,222.8
XS Rating Curve= 0 ,0
Exp/Cntr(USF)=0,0
Exp/Cntr=0.5,0.3

Type RM Length L Ch R = 1 ,17230   ,53.2,53.1,53.5
XS GIS Cut Line= 2
2310546.63208097550958.6829087522310675.74605441551509.914450532
#Sta/Elev= 30
       0    2794     6.7  2790.6    10.8 2789.22    13.3 2788.83    23.1 2788.23
    76.6 2783.51    97.1 2782.58   109.4 2781.59   142.2 2780.78   154.6 2779.83
   162.8 2779.87   179.2 2781.76   187.4  2782.1   191.5 2781.65   195.7 2780.48
   203.9 2779.81   217.12780.259   228.5  2780.4   236.7 2780.94   261.4 2780.57
   290.1 2781.37     350 2781.88   380.5 2782.79   419.7 2785.46   470.9 2786.11
   522.6 2788.28     526 2788.64   536.6 2790.53   559.2 2792.45   566.2  2792.8
#Mann= 8 ,-1,0
       0     .06       0     150     .07       0   195.7    .045       0
   217.1     .07       0     250     .05       0     350     .06       0
     450     .07       0     550     .06       0
#XS Ineff= 2 , 0
          188.41 2783.98  233.88         2783.96
Permanent Ineff=
       F       F
Bank Sta=195.7,217.1
XS Rating Curve= 0 ,0
Exp/Cntr(USF)=0,0
Exp/Cntr=0.5,0.3

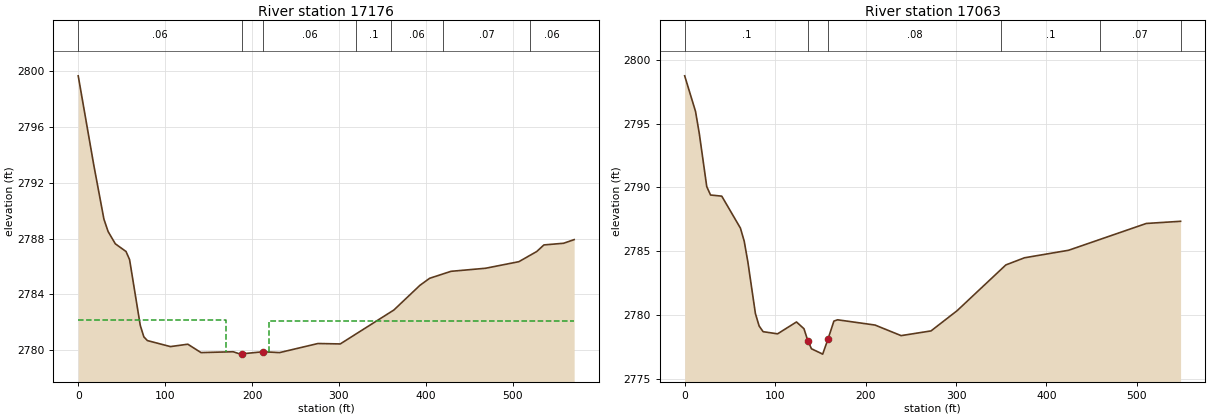
Type RM Length L Ch R = 1 ,17176   ,114.6,113.9,114
XS GIS Cut Line= 2
2310498.05296402550983.6626515132310628.82926436551539.094578779
#Sta/Elev= 30
       0 2799.65      18 2793.23    29.6 2789.38    34.4  2788.5    42.7 2787.62
      55 2787.07    59.1 2786.49    71.4 2781.78    75.5 2780.96    79.6 2780.69
   106.1 2780.26   126.1 2780.43   141.3 2779.83   178.3 2779.89   186.5 2779.72
   188.52779.742   212.6 2779.89   231.7 2779.83   275.8 2780.48   301.5 2780.45
   363.2 2782.88   393.2 2784.65   404.3 2785.15   428.9 2785.65   468.7 2785.87
     507 2786.34   527.6 2787.07   535.8 2787.54   558.5 2787.66   570.6 2787.92
#Mann= 7 ,-1,0
       0     .06       0   188.5    .045       0   212.6     .06       0
     320      .1       0     360     .06       0     420     .07       0
     520     .06       0
#XS Ineff= 2 , 0
          169.75 2782.16  219.67         2782.08
Permanent Ineff=
       F       F
Bank Sta=188.5,212.6
XS Rating Curve= 0 ,0
Exp/Cntr(USF)=0,0
Exp/Cntr=0.5,0.3

Type RM Length L Ch R = 1 ,17063   ,324.1,330,327.4
XS GIS Cut Line= 3
2310394.04907034551053.5471553772310507.11914125551487.974269917
2310580.91224016551554.626101189
#Sta/Elev= 30
       0 2798.74      12 2795.95    16.2  2794.2    24.4 2790.06    28.6  2789.4
      41 2789.31    61.6 2786.81    65.8 2785.79    69.9 2784.14    78.2 2780.11
    82.3 2779.14    86.7 2778.69   102.7 2778.52   123.6 2779.45   131.9 2778.92
   136.2 2777.97   140.2 2777.35   152.6 2776.93   158.62778.141     165 2779.52
   169.1 2779.62   210.4 2779.21   239.3 2778.38   272.4 2778.75   301.3 2780.34
   355.1 2783.92   375.7 2784.48   424.5 2785.07   510.4 2787.17   548.3 2787.34
#Mann= 6 ,-1,0
       0      .1       0   136.2    .045       0   158.6     .08       0
     350      .1       0   458.9     .07       0  548.34     .06       0
Bank Sta=136.2,158.6
XS Rating Curve= 0 ,0
Exp/Cntr(USF)=0,0
Exp/Cntr=0.3,0.1