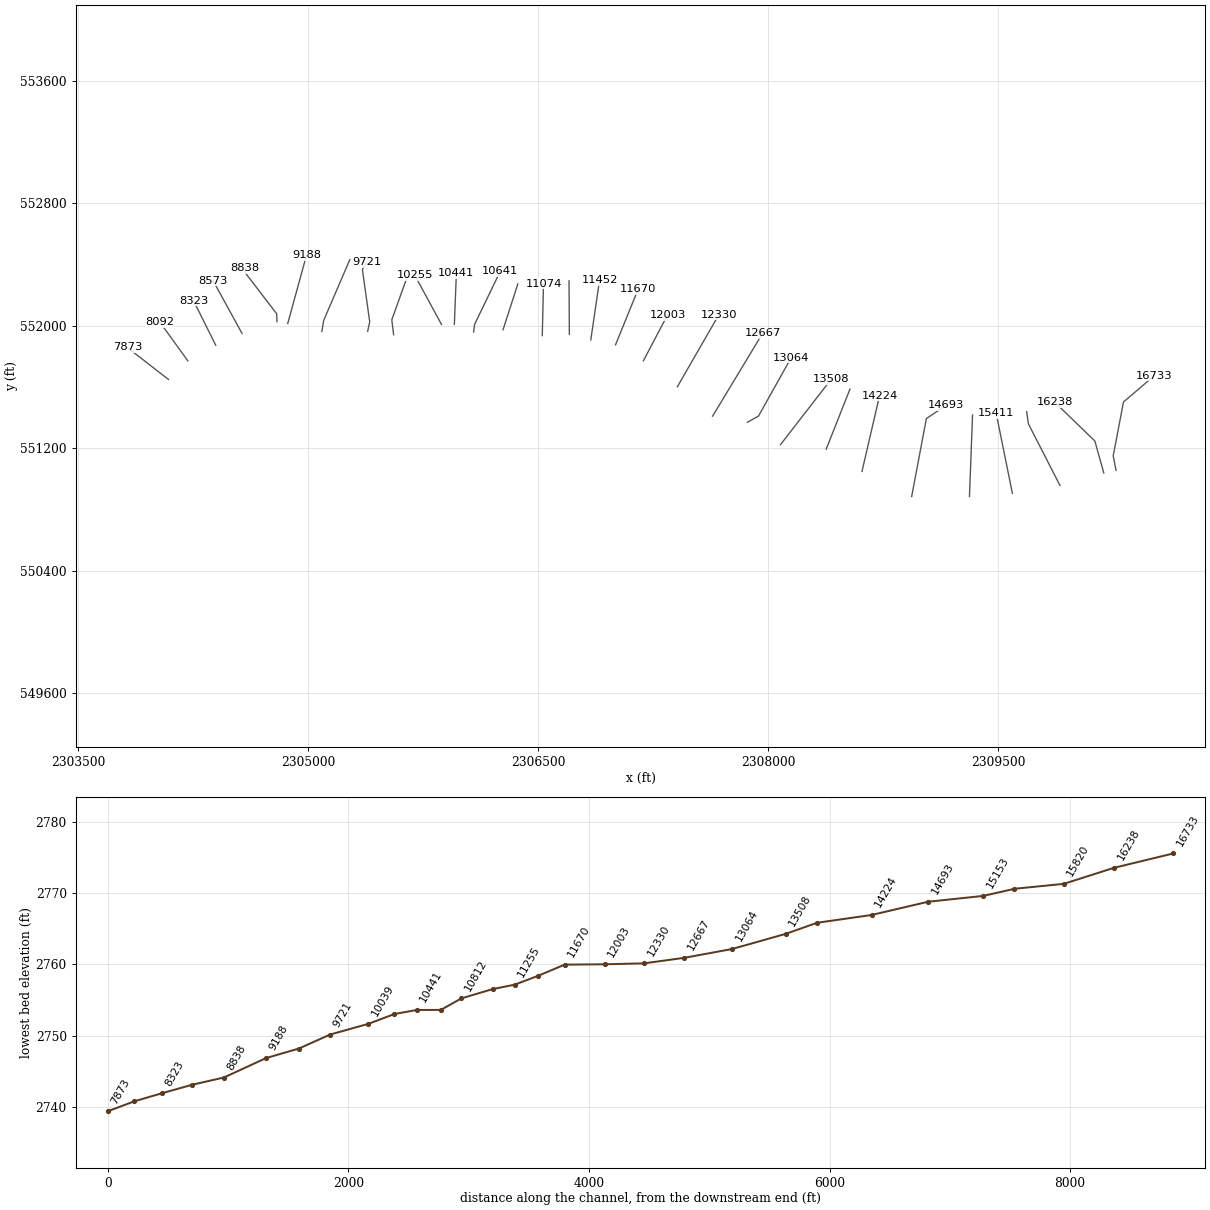
HEC-RAS study BRSHRN.prj: BRSHRN

--- BRSHRN.g01 (geometry) --- (continued)

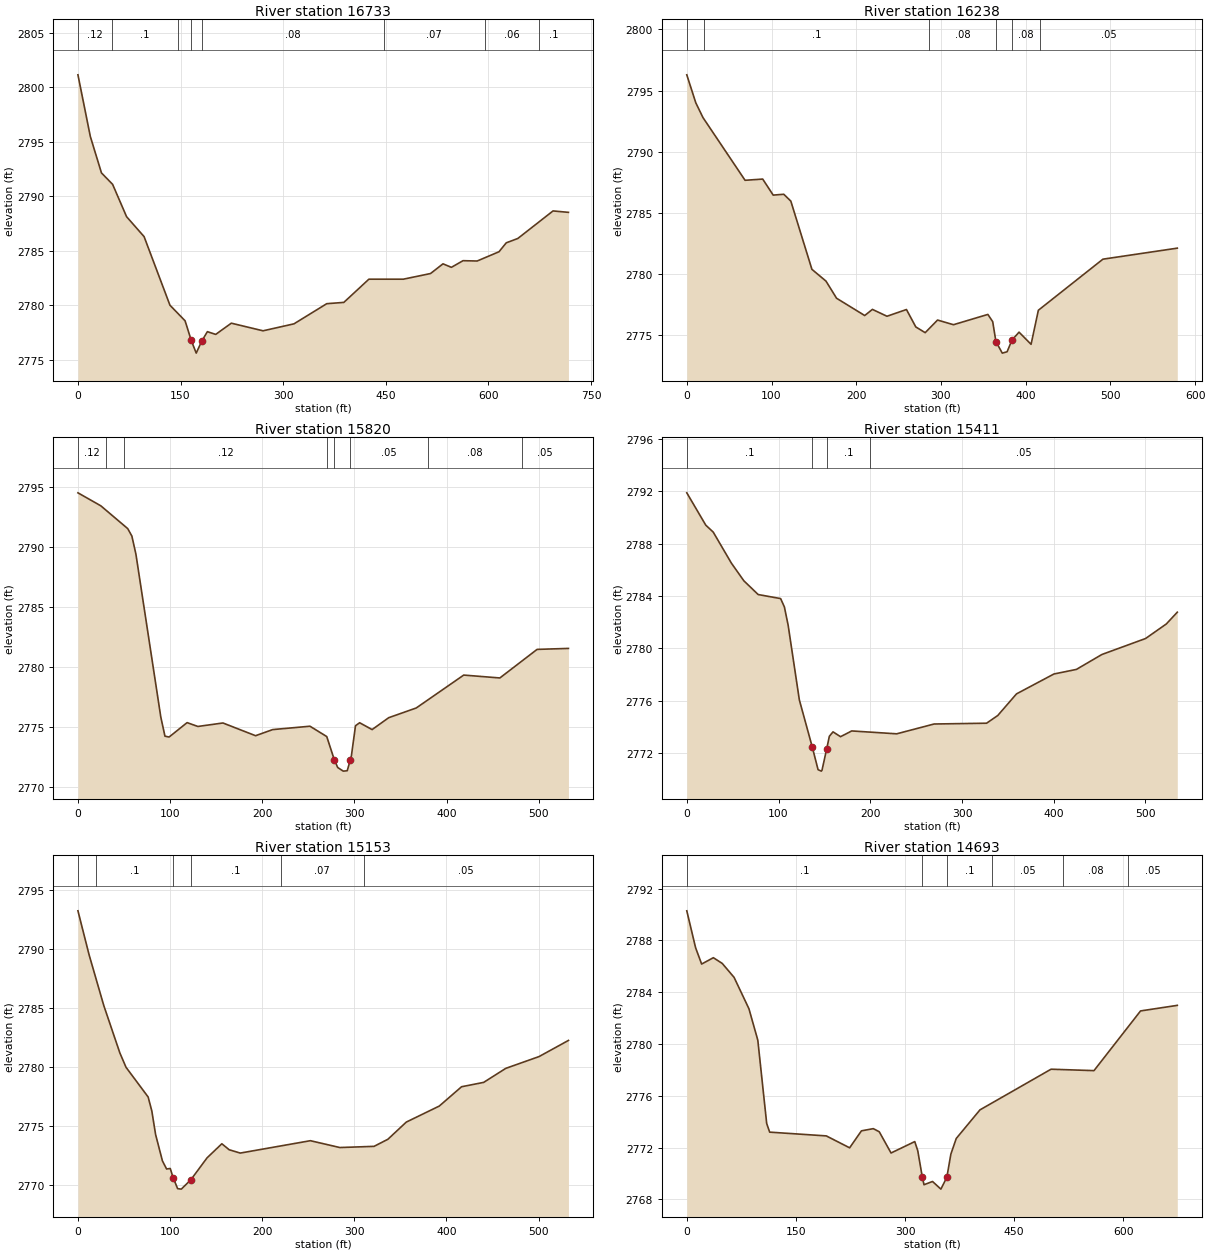
Type RM Length L Ch R = 1 ,16733   ,472.4,495.1,505.3
XS GIS Cut Line= 4
2310269.19010119551055.432507611 2310250.7414884551150.368133767
2310317.66051564 551501.728842492310517.28573329551672.325791578
#Sta/Elev= 30
       0 2801.15    18.1 2795.49    34.4 2792.14    50.7 2791.09    71.1 2788.12
    96.7 2786.29   134.5 2779.99   156.6 2778.56   165.62776.766   172.9 2775.59
   180.92776.683   189.2 2777.56   201.4 2777.31   224.2 2778.34   270.6 2777.64
   315.8 2778.28   363.7 2780.13   388.7 2780.25   425.3 2782.38   475.6 2782.38
   515.4  2782.9   533.6 2783.79   545.9 2783.47   562.9 2784.08   583.5 2784.05
   615.5  2784.9   626.1 2785.72     643 2786.12   694.5 2788.65     717 2788.52
#Mann= 8 ,-1,0
       0     .12       0      50      .1       0  146.71     .08       0
   165.6    .045       0   180.9     .08       0  446.71     .07       0
  594.39     .06       0  674.39      .1       0
Bank Sta=165.6,180.9
XS Rating Curve= 0 ,0
Exp/Cntr(USF)=0,0
Exp/Cntr=0.3,0.1

Type RM Length L Ch R = 1 ,16238   ,419.4,417.5,410.8
XS GIS Cut Line= 3
2310189.33273144551038.9505362482310130.89972533551247.343632063
 2309870.2614159551499.443114394
#Sta/Elev= 30
       0 2796.28    10.6    2794    19.1 2792.79    68.8 2787.67    89.6 2787.77
     102 2786.46   114.5 2786.53   122.8 2785.97   147.7  2780.4   164.3 2779.44
   176.8 2778.04     210 2776.63   219.1 2777.13   236.3 2776.57   259.3 2777.12
   270.3  2775.7   281.4 2775.23     296 2776.26   314.8 2775.88   355.4 2776.72
   361.1 2776.13   364.9  2774.5   372.4 2773.56   378.1 2773.67   383.92774.635
   392.2 2775.27   406.4 2774.28     415 2777.06   491.2 2781.23     579 2782.13
#Mann= 6 ,-1,0
       0     .12       0      20      .1       0  286.43     .08       0
   364.9    .045       0   383.9     .08       0  416.43     .05       0
Bank Sta=364.9,383.9
XS Rating Curve= 0 ,0
Exp/Cntr(USF)=0,0
Exp/Cntr=0.3,0.1

Type RM Length L Ch R = 1 ,15820   ,410.7,409.1,403.9
XS GIS Cut Line= 3
2309903.46977981550957.1541236792309697.75425119 551358.78920336
2309686.32561071 551438.78968671
#Sta/Elev= 30
       0 2794.49    24.8 2793.41      54 2791.51    58.5 2790.89    62.9 2789.38
    89.9 2775.81    94.4 2774.22    98.9 2774.15   118.4 2775.35   130.1 2775.03
   157.3 2775.32   192.7 2774.26   211.3 2774.77   251.7 2775.05   269.9 2774.19
   278.1 2772.26   281.8 2771.61   287.8 2771.31   292.1 2771.34   295.4 2772.21
   296.7 2772.61   301.1 2775.09   305.6 2775.34   319.1 2774.77   337.1 2775.76
     367 2776.57   418.5 2779.31   457.7 2779.07   498.1 2781.45   532.1 2781.53
#Mann= 8 ,-1,0
       0     .12       0      30      .1       0      50     .12       0
     270     .05       0   278.1    .045       0   295.4     .05       0
     380     .08       0  481.25     .05       0
Bank Sta=278.1,295.4
XS Rating Curve= 0 ,0
Exp/Cntr(USF)=0,0
Exp/Cntr=0.3,0.1

Type RM Length L Ch R = 1 ,15411   ,261.4,258.3,254.6
XS GIS Cut Line= 2
2309593.26382395550904.908910062 2309487.1407338551428.993709157
#Sta/Elev= 30
       0 2791.88    20.7 2789.41    28.8 2788.88    48.7  2786.5    62.2 2785.16
    77.8 2784.11   102.3  2783.8   106.4 2783.16   110.5 2781.76   122.7 2776.06
   136.9 2772.43   143.1 2770.73   146.6 2770.62   147.4 2770.69   152.5 2772.32
   155.4 2773.28   159.4 2773.62   167.6 2773.25   179.8 2773.69   228.8 2773.47
   269.6 2774.22   326.8 2774.28     339 2774.87   359.4 2776.52   400.2 2778.04
   424.7 2778.39   452.5 2779.53   500.1 2780.75   522.7 2781.86   534.7 2782.76
#Mann= 4 ,-1,0
       0      .1       0   136.9    .045       0   152.5      .1       0
     200     .05       0
Bank Sta=136.9,152.5
XS Rating Curve= 0 ,0
Exp/Cntr(USF)=0,0
Exp/Cntr=0.3,0.1

Type RM Length L Ch R = 1 ,15153   ,451.9,459.4,458
XS GIS Cut Line= 2
2309313.15687154550885.0614526672309333.23195419551417.051142933
#Sta/Elev= 30
       0 2793.24    12.1 2789.51    28.1 2785.19    45.5 2781.18    52.2 2779.96
    76.2 2777.44    80.2 2776.25    84.3 2774.25    91.7 2772.02    96.2 2771.33
   100.2 2771.37   103.3  2770.6   108.2 2769.66   112.2 2769.62   122.6 2770.42
   140.2 2772.28   156.2 2773.47   164.2 2772.96   176.2 2772.68   252.3 2773.73
   284.3 2773.15   321.4 2773.25   336.4 2773.85   356.4 2775.31   392.2 2776.67
   416.4 2778.31   440.4 2778.68   464.4 2779.87   500.5 2780.87   532.4 2782.24
#Mann= 6 ,-1,0
       0     .12       0      20      .1       0   103.3    .045       0
   122.6      .1       0     220     .07       0     310     .05       0
Bank Sta=103.3,122.6
XS Rating Curve= 0 ,0
Exp/Cntr(USF)=0,0
Exp/Cntr=0.3,0.1

Type RM Length L Ch R = 1 ,14693   ,464.3,469.6,467.3
XS GIS Cut Line= 3
 2308936.2211034550885.2871584862309032.01356584551393.312532959
2309162.24081161551481.238922774
#Sta/Elev= 30
       0 2790.29    12.1 2787.44    20.4 2786.18    36.5 2786.67    48.7 2786.23
      65 2785.15    85.4 2782.73    97.6  2780.3   109.8 2773.87   113.9  2773.2
   191.7 2772.91   223.8 2771.99     240  2773.3   256.3 2773.47   264.5 2773.23
   280.7 2771.59   313.3 2772.47   317.4 2771.77   323.6 2769.75     326 2769.14
   337.7 2769.39   349.2  2768.8   357.42769.717   362.9  2771.5   370.3 2772.71
   402.9 2774.92   500.6 2778.06   559.6 2777.95   623.6 2782.56   674.1 2782.99
#Mann= 6 ,-1,0
       0      .1       0   323.6    .045       0   357.4      .1       0
     420     .05       0  516.98     .08       0  606.98     .05       0
Bank Sta=323.6,357.4
XS Rating Curve= 0 ,0
Exp/Cntr(USF)=0,0
Exp/Cntr=0.3,0.1

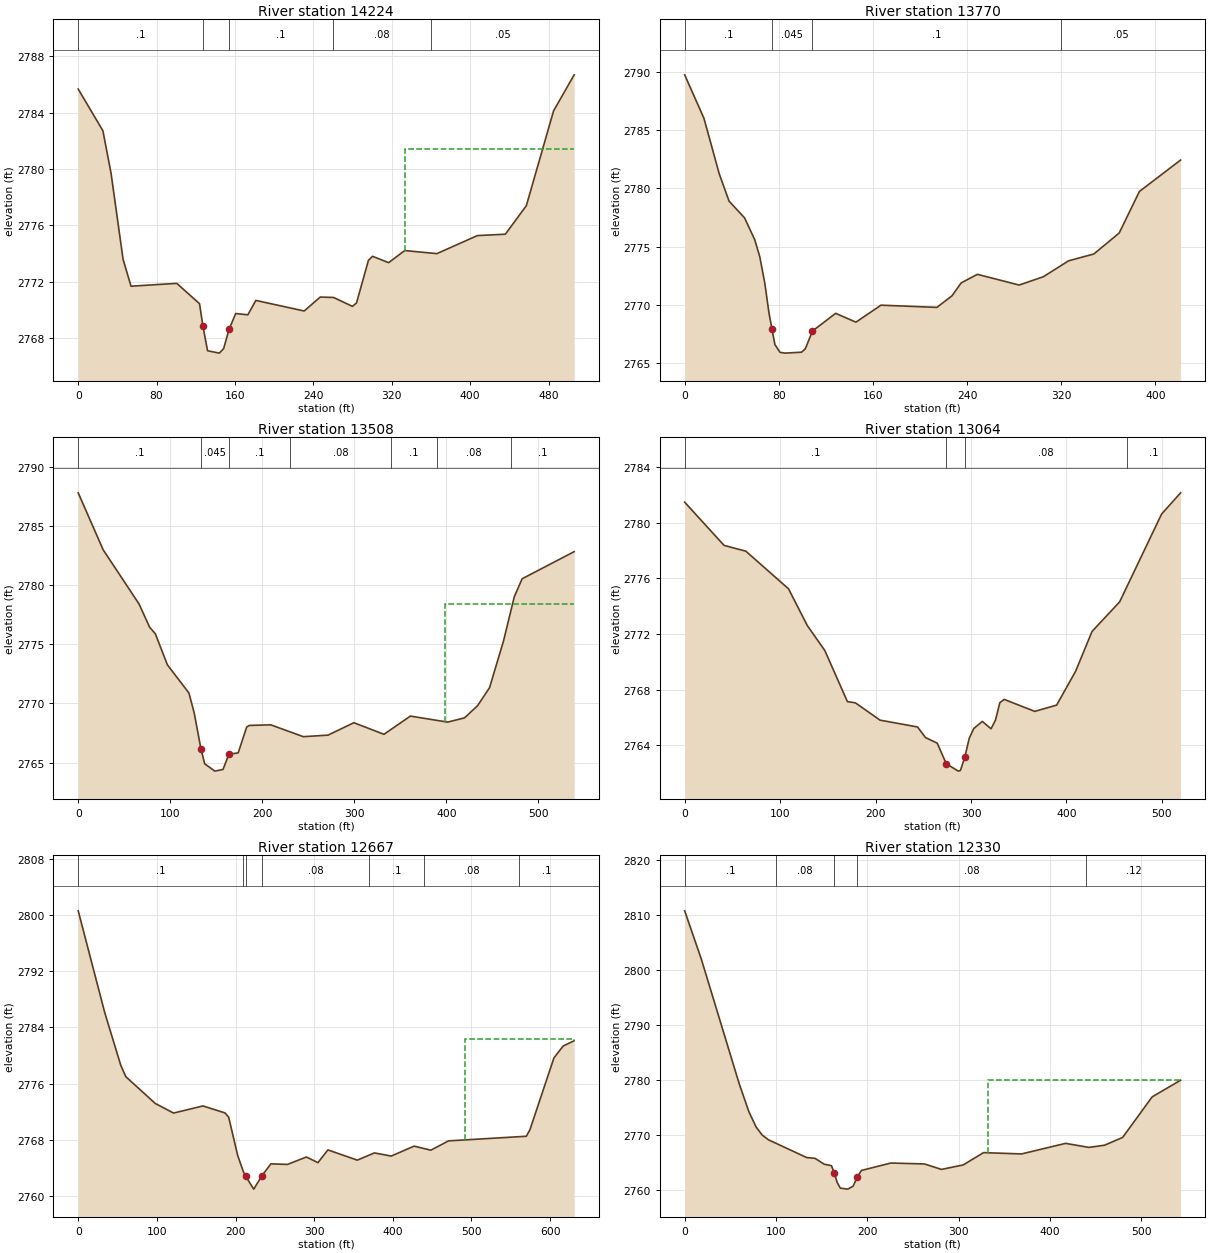
Type RM Length L Ch R = 1 ,14224   ,449.9,453.8,444.1
XS GIS Cut Line= 2
2308612.03340571551048.583247509 2308726.3198105551541.647451019
#Sta/Elev= 30
       0 2785.68    25.2 2782.72    33.5 2779.71    45.8 2773.59    53.9 2771.69
   100.6 2771.89   123.8 2770.45   127.3 2768.84     132 2767.11     144 2766.94
   148.4 2767.26     154 2768.64   160.7 2769.75   173.1 2769.66   181.3 2770.68
   230.6 2769.93     247 2770.92   260.6 2770.89   279.8 2770.26     284  2770.5
   296.2 2773.53   300.4 2773.81   316.8 2773.36   333.2 2774.22     366    2774
   407.3 2775.28   435.9 2775.38   457.3  2777.4   485.1 2784.13   506.1 2786.69
#Mann= 5 ,-1,0
       0      .1       0   127.3    .045       0     154      .1       0
     260     .08       0     360     .05       0
#XS Ineff= 2 , 0
                          333.33         2781.44
Permanent Ineff=
       F       F
Bank Sta=127.3,154
XS Rating Curve= 0 ,0
Exp/Cntr(USF)=0,0
Exp/Cntr=0.3,0.1

Type RM Length L Ch R = 1 ,13770   ,269.4,262.3,258.8
XS GIS Cut Line= 2
2308378.56260736551193.8902478812308533.66558529551585.729350008
#Sta/Elev= 30
       0 2789.75    16.4 2786.01    29.3 2781.27    37.7  2778.9    50.9 2777.46
    59.5 2775.59    63.8 2774.13    68.1 2771.84    71.6 2769.31    74.2 2767.89
    76.7 2766.57      81 2765.91    85.3 2765.84    99.3 2765.92   102.5 2766.21
   108.6 2767.74   128.3 2769.26   145.5  2768.5   166.8 2769.96   214.3 2769.77
   227.2 2770.77   234.9 2771.87   248.7 2772.61   284.2 2771.69   304.7  2772.4
   326.2 2773.77   347.7 2774.36   369.2 2776.16   386.4 2779.73   421.4 2782.43
#Mann= 4 ,-1,0
       0      .1       0    74.2    .045       0   108.6      .1       0
     320     .05       0
Bank Sta=74.2,108.6
XS Rating Curve= 0 ,0
Exp/Cntr(USF)=0,0
Exp/Cntr=0.3,0.1

Type RM Length L Ch R = 1 ,13508   ,442.7,443.5,441.7
XS GIS Cut Line= 2
2308080.88178181551223.7557863392308410.67969277551649.880809902
#Sta/Elev= 30
       0 2787.79    27.1 2782.98    66.1  2778.4    77.5 2776.45    83.8 2775.88
    96.9 2773.26   120.3 2770.88     126  2769.2   133.3 2766.18   137.4  2764.9
   148.5 2764.28   157.3 2764.42   163.7 2765.71   173.8 2765.82     183    2768
   185.8 2768.14   209.2 2768.19   244.6 2767.19   271.4 2767.32   299.5 2768.37
   332.2 2767.39   360.9 2768.93   401.4 2768.42   419.7 2768.78   433.9 2769.81
   446.9 2771.33   462.1 2775.29   473.8 2779.02   482.3 2780.53   538.8 2782.82
#Mann= 7 ,-1,0
       0      .1       0   133.3    .045       0   163.7      .1       0
     230     .08       0     340      .1       0     390     .08       0
     470      .1       0
#XS Ineff= 2 , 0
                           398.4         2778.39
Permanent Ineff=
       F       F
Bank Sta=133.3,163.7
XS Rating Curve= 0 ,0
Exp/Cntr(USF)=0,0
Exp/Cntr=0.3,0.1

Type RM Length L Ch R = 1 ,13064   ,394.9,397.3,394.4
XS GIS Cut Line= 3
2307864.14577845551369.2097263742307936.91356504551409.667113669
2308149.82913715551790.534720936
#Sta/Elev= 30
       0 2781.47    41.2 2778.37    64.1 2777.95   108.8 2775.25   128.5 2772.61
   146.9 2770.81   170.5 2767.15   178.9 2767.06   204.7 2765.82     244 2765.33
   252.3 2764.57   264.6 2764.17   274.12762.688   286.7 2762.16   288.9 2762.21
   293.5 2763.16   298.1 2764.51   302.8 2765.21   311.8 2765.73     321  2765.2
   325.6 2765.82   330.2 2767.07   334.7 2767.31   366.8 2766.45   389.7  2766.9
   409.6 2769.33   426.8 2772.19   455.7 2774.31   499.7 2780.62   519.6 2782.14
#Mann= 4 ,-1,0
       0      .1       0   274.1    .045       0   293.5     .08       0
  463.26      .1       0
Bank Sta=274.1,293.5
XS Rating Curve= 0 ,0
Exp/Cntr(USF)=0,0
Exp/Cntr=0.3,0.1

Type RM Length L Ch R = 1 ,12667   ,334.5,336.3,335.3
XS GIS Cut Line= 2
2307637.60021606551409.3465808882307963.36270443551949.229557298
#Sta/Elev= 30
       0 2800.66    33.8  2786.1    54.2 2778.58    60.5 2776.98    97.9 2773.16
   121.2 2771.78   158.6  2772.8   186.7  2771.8   191.3  2771.2   202.8 2765.72
     210 2763.42     2132762.734   223.2 2760.92   233.4  2762.8     245 2764.53
   266.1 2764.45   290.2 2765.51   304.8  2764.7   317.5 2766.52   354.9 2765.06
   376.6 2766.09     398 2765.64   427.1 2767.06   448.3 2766.48   470.9 2767.81
   569.8 2768.47   574.4 2769.41   604.9 2779.66   616.6 2781.35   630.6 2782.11
#Mann= 7 ,-1,0
       0      .1       0     210     .08       0     213    .045       0
   233.4     .08       0     370      .1       0     440     .08       0
     560      .1       0
#XS Ineff= 2 , 0
                          491.69         2782.33
Permanent Ineff=
       F       F
Bank Sta=213,233.4
XS Rating Curve= 0 ,0
Exp/Cntr(USF)=0,0
Exp/Cntr=0.3,0.1

Type RM Length L Ch R = 1 ,12330   ,325.6,327.5,327.5
XS GIS Cut Line= 2
2307407.93077716551601.4233742722307679.03445595552072.218055478
#Sta/Elev= 30
       0 2810.68    18.2 2801.93    59.7  2779.3    70.3 2774.21    78.2 2771.44
    84.9 2769.96      92 2769.08   133.6 2765.88   142.8 2765.73   152.8 2764.67
   160.8  2764.4     164 2763.05     167 2761.38   170.5 2760.32   178.7 2760.14
   184.5 2760.67     189 2762.31   193.6 2763.53   225.9 2764.88   262.8 2764.71
   281.3 2763.72   305.1 2764.53   327.4 2766.77     369 2766.53   417.3 2768.45
   442.8 2767.72   459.9 2768.11   479.8 2769.53   512.1 2776.89   543.3 2779.92
#Mann= 5 ,-1,0
       0      .1       0     100     .08       0     164    .045       0
     189     .08       0     440     .12       0
#XS Ineff= 2 , 0
                          332.17         2779.95
Permanent Ineff=
       F       F
Bank Sta=164,189
XS Rating Curve= 0 ,0
Exp/Cntr(USF)=0,0
Exp/Cntr=0.3,0.1

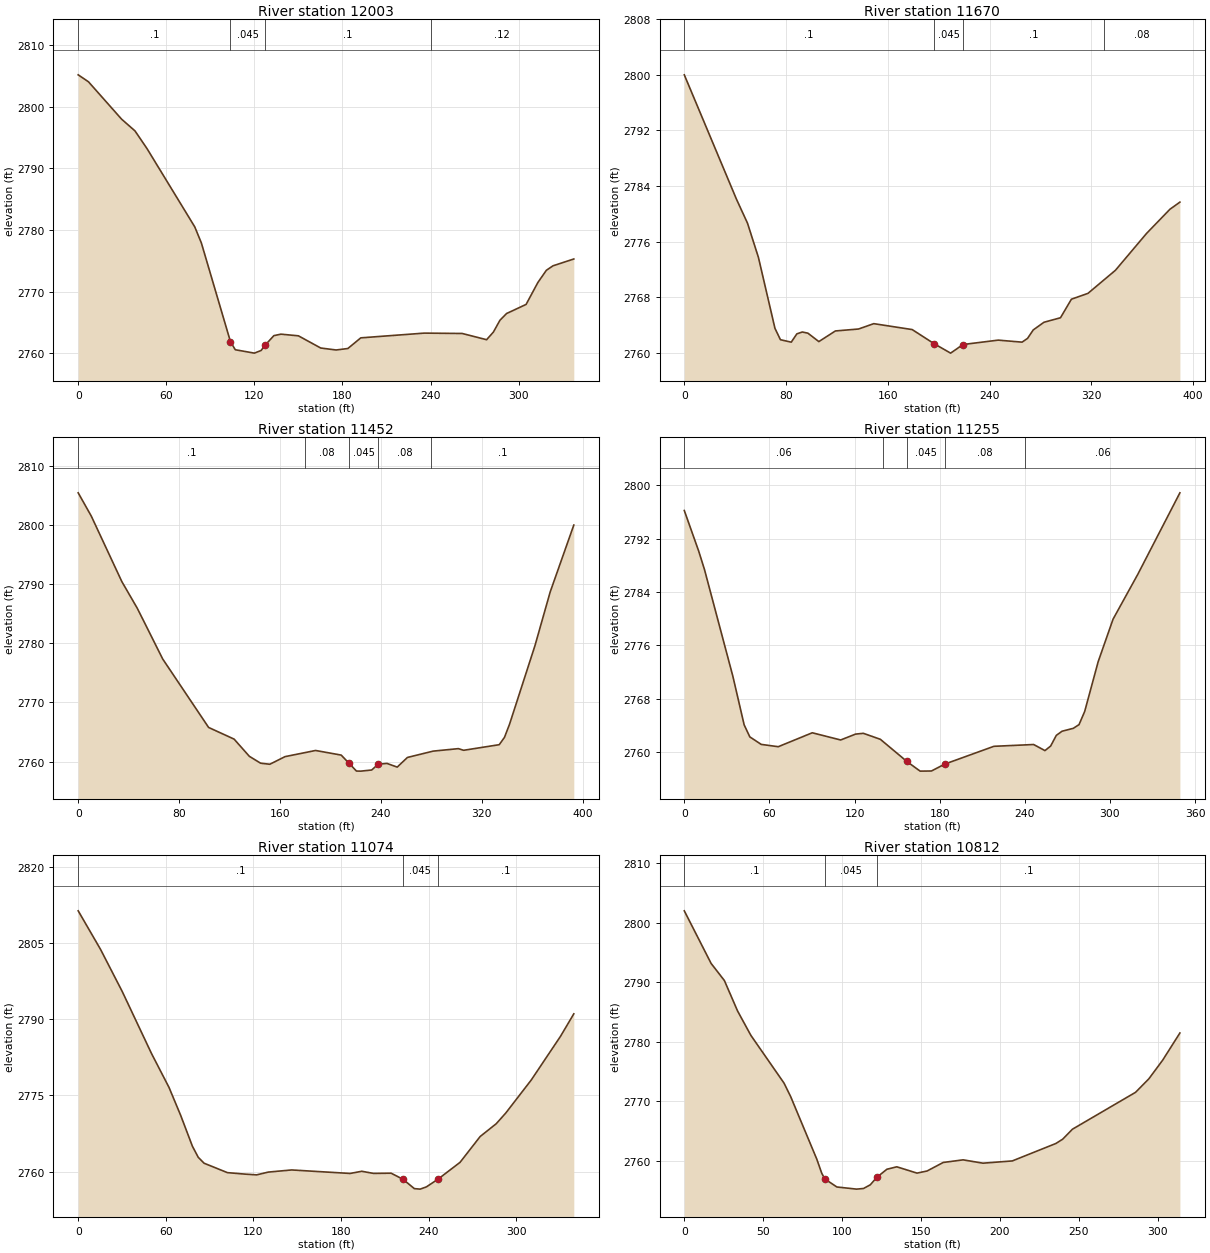
Type RM Length L Ch R = 1 ,12003   ,332,332.5,334.8
XS GIS Cut Line= 2
2307186.33045501551770.957484621  2307343.572044552069.693008068
#Sta/Elev= 30
       0 2805.21       7 2804.08    29.6    2798    38.7  2796.1    46.9 2793.22
    79.4 2780.52    83.9 2777.91   103.7 2761.89     107 2760.56     120 2760.01
   124.6 2760.44   127.4 2761.32   133.3 2762.85   138.1 2763.09     150 2762.82
   165.2 2760.84   175.7 2760.52   183.7 2760.76   192.5 2762.49   235.8 2763.26
   261.6  2763.2   278.2 2762.19   282.8 2763.42   287.3 2765.35   291.8 2766.44
   305.1 2767.92   313.1 2771.47   318.9 2773.46   323.4 2774.19   337.6  2775.3
#Mann= 4 ,-1,0
       0      .1       0   103.7    .045       0   127.4      .1       0
     240     .12       0
Bank Sta=103.7,127.4
XS Rating Curve= 0 ,0
Exp/Cntr(USF)=0,0
Exp/Cntr=0.3,0.1

Type RM Length L Ch R = 1 ,11670   ,214.6,218.5,222.5
XS GIS Cut Line= 2
2307004.58140141551875.1719669962307151.37412505552236.202719718
#Sta/Elev= 30
       0 2800.01      41 2782.12    49.7 2778.66    58.3 2773.73    71.3 2763.52
    75.6 2761.89    84.1 2761.54    88.5 2762.73    92.8    2763    97.2 2762.83
   105.8 2761.62   118.8 2763.15     137 2763.43     149  2764.2   179.2 2763.35
   196.5 2761.31   209.4 2759.96   219.2  2761.2   246.8 2761.83   265.6 2761.54
   269.9 2762.08   274.4  2763.3   282.8  2764.4   295.8 2765.05   304.4 2767.72
   317.4 2768.56     339 2771.88   363.5 2777.19   381.9 2780.67   389.7 2781.69
#Mann= 4 ,-1,0
       0      .1       0   196.5    .045       0   219.2      .1       0
     330     .08       0
Bank Sta=196.5,219.2
XS Rating Curve= 0 ,0
Exp/Cntr(USF)=0,0
Exp/Cntr=0.3,0.1

Type RM Length L Ch R = 1 ,11452   ,194.3,197.1,197
XS GIS Cut Line= 2
2306843.24165111551906.9109342682306900.10730081552295.713283354
#Sta/Elev= 30
       0 2805.43    10.4 2801.49    34.6 2790.43    46.8 2785.94      67 2777.35
   103.4 2765.78   123.6 2763.81   135.7  2760.9   144.6 2759.74   151.9 2759.56
     164 2760.85   188.2 2761.89   208.5 2761.11   214.7 2759.73   220.6 2758.41
   224.1  2758.4   232.7 2758.59   237.8 2759.57   244.8  2759.7   252.9 2759.08
     261 2760.71   281.4 2761.78   301.4  2762.2   305.5 2761.92   333.8 2762.87
   337.9 2764.09   341.9 2766.29   362.1  2779.6   374.2 2788.69   392.9 2799.98
#Mann= 5 ,-1,0
       0      .1       0     180     .08       0   214.7    .045       0
   237.8     .08       0     280      .1       0
Bank Sta=214.7,237.8
XS Rating Curve= 0 ,0
Exp/Cntr(USF)=0,0
Exp/Cntr=0.3,0.1

Type RM Length L Ch R = 1 ,11255   ,182.2,181,181
XS GIS Cut Line= 2
2306703.39612684551943.0183084032306701.38861857552292.324746539
#Sta/Elev= 30
       0 2796.22    10.2  2790.1    14.2 2787.39    34.2 2771.39    42.2 2764.07
    46.2 2762.27    54.2 2761.15    66.2  2760.8    90.2 2762.89   110.2 2761.81
   120.7 2762.69   126.2 2762.81   138.2 2761.91   156.92758.585   166.2 2757.14
   174.2 2757.16   183.62758.197   218.2 2760.86   246.2 2761.13   254.2 2760.22
   258.2  2760.9   262.2  2762.5   266.2 2763.12   274.2 2763.56   278.2 2764.11
   282.2 2766.09   291.7 2773.55   302.2 2779.93   319.6 2786.64   349.3 2798.87
#Mann= 5 ,-1,0
       0     .06       0     140     .08       0   156.9    .045       0
   183.6     .08       0     240     .06       0
Bank Sta=156.9,183.6
XS Rating Curve= 0 ,0
Exp/Cntr(USF)=0,0
Exp/Cntr=0.3,0.1

Type RM Length L Ch R = 1 ,11074   ,264.7,261.3,246.7
XS GIS Cut Line= 2
 2306526.7353995551934.9882753422306534.76543256552274.257172153
#Sta/Elev= 30
       0  2811.4    15.3  2803.8    30.2 2795.47    50.2 2783.27    62.2 2776.58
    70.2 2771.06    78.2    2765    82.2 2762.81    86.2 2761.64   102.2 2759.78
   114.2 2759.49   122.2 2759.34   130.2 2759.89   146.2 2760.31   186.2 2759.62
   194.2 2760.05   202.2 2759.63   214.3 2759.67   222.4 2758.48   230.2 2756.63
   234.2 2756.53   238.5 2756.98   246.3 2758.47   261.5 2761.81   275.3 2766.91
   286.3 2769.43   292.8 2771.53   310.3 2778.06   330.3 2786.66   339.4 2791.09
#Mann= 3 ,-1,0
       0      .1       0   222.4    .045       0   246.3      .1       0
Bank Sta=222.4,246.3
XS Rating Curve= 0 ,0
Exp/Cntr(USF)=0,0
Exp/Cntr=0.3,0.1

Type RM Length L Ch R = 1 ,10812   ,172.9,171.2,167.3
XS GIS Cut Line= 2
2306270.61778324551973.0337827522306367.15714203552271.909057899
#Sta/Elev= 30
       0 2801.99      17 2793.15    25.4 2790.28    33.8 2785.14    42.2 2781.06
    63.2 2773.04    67.4 2770.78      84 2760.24    87.1  2757.9      892756.944
    96.7 2755.58   109.2 2755.22   113.6 2755.33   117.9 2755.95     122  2757.2
   128.4 2758.56   134.7 2758.97   147.5 2757.91   153.9 2758.27   164.1  2759.7
   176.7 2760.14   189.3 2759.58   207.9 2759.96   235.5 2762.89   239.8 2763.61
     246 2765.29     286 2771.49   294.4 2773.75   303.2  2776.9   314.1 2781.46
#Mann= 3 ,-1,0
       0      .1       0      89    .045       0     122      .1       0
Bank Sta=89,122
XS Rating Curve= 0 ,0
Exp/Cntr(USF)=0,0
Exp/Cntr=0.3,0.1

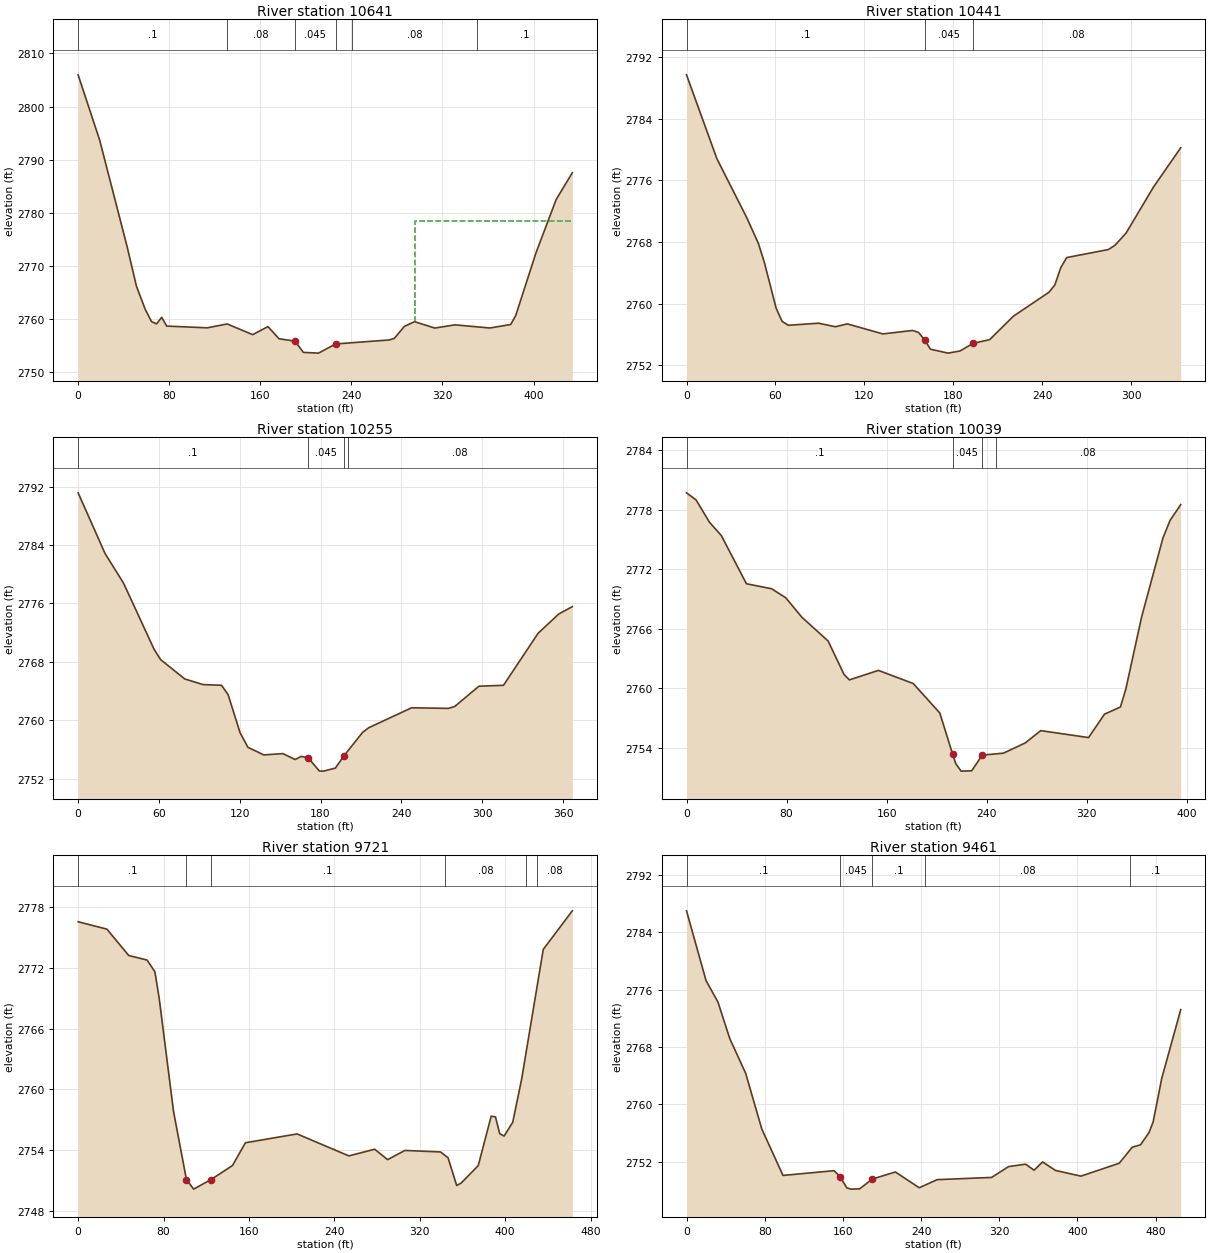
Type RM Length L Ch R = 1 ,10641   ,193.8,200.6,210.9
XS GIS Cut Line= 3
2306078.86152264551958.4867560862306085.47380749552008.740120934
2306252.10338567 552353.90139002
#Sta/Elev= 30
       0 2805.98    18.9  2793.7    43.1 2773.58    51.2 2766.21      59 2761.81
    64.5 2759.53    68.9  2759.1    73.4 2760.34    77.8 2758.69   113.4 2758.36
   130.9 2759.09   153.3 2757.08   166.7 2758.59   176.5  2756.3   190.52755.856
   197.8 2753.74   211.1  2753.6   226.2 2755.33   273.3 2756.08   277.7 2756.38
   286.6 2758.65   295.5 2759.52   313.2 2758.32     331 2758.92   361.6 2758.33
   379.9 2758.99   384.3 2760.66   402.1 2772.47   419.8  2782.5     434 2787.54
#Mann= 6 ,-1,0
       0      .1       0  130.69     .08       0   190.5    .045       0
   226.2      .1       0  240.69     .08       0  350.69      .1       0
#XS Ineff= 2 , 0
                          296.14         2778.54
Permanent Ineff=
       F       F
Bank Sta=190.5,226.2
XS Rating Curve= 0 ,0
Exp/Cntr(USF)=0,0
Exp/Cntr=0.3,0.1

Type RM Length L Ch R = 1 ,10441   ,174.4,185.3,194.6
XS GIS Cut Line= 2
2305953.22811052552008.7401209342305966.45268021552341.999277293
#Sta/Elev= 30
       0 2789.67    20.5 2778.79    40.5 2771.21    48.5 2767.81    52.5 2765.37
    60.5  2759.4    64.5 2757.71    68.7  2757.2    89.1 2757.47   100.5 2757.01
   108.5 2757.38   132.5 2756.08   152.6 2756.53   156.6 2756.27   160.6 2755.33
   164.6  2754.1   176.5 2753.59   184.6 2753.87   193.3 2754.85   204.6 2755.34
   220.6 2758.38   244.6 2761.48   248.6 2762.44   252.6 2764.69   256.6 2765.98
   284.7 2767.02   289.2 2767.58   296.7 2769.17   315.1 2775.11   333.5 2780.21
#Mann= 3 ,-1,0
       0      .1       0   160.6    .045       0   193.3     .08       0
Bank Sta=160.6,193.3
XS Rating Curve= 0 ,0
Exp/Cntr(USF)=0,0
Exp/Cntr=0.3,0.1

Type RM Length L Ch R = 1 ,10255   ,230.3,216.2,200.8
XS GIS Cut Line= 2
2305869.59005417552007.5678689532305694.62899708552330.115123857
#Sta/Elev= 30
       0 2791.16      20 2782.84    33.7 2778.79    56.4 2769.72    61.2 2768.31
    79.2 2765.65    92.8 2764.88   106.5 2764.78   111.4 2763.48   120.2  2758.3
   126.1 2756.28   137.9 2755.24     152 2755.42   161.1 2754.61   165.7 2755.04
   170.8 2754.84   179.1 2753.04   182.2 2753.02     191 2753.44   197.5 2755.15
   211.2 2758.33   215.7 2758.96   247.6  2761.7   274.9 2761.62   279.6 2761.88
   297.6 2764.66   315.8 2764.78   341.5 2771.91   356.8 2774.55   366.9 2775.56
#Mann= 4 ,-1,0
       0      .1       0   170.8    .045       0   197.5      .1       0
     200     .08       0
Bank Sta=170.8,197.5
XS Rating Curve= 0 ,0
Exp/Cntr(USF)=0,0
Exp/Cntr=0.3,0.1

Type RM Length L Ch R = 1 ,10039   ,310.2,317.7,327.2
XS GIS Cut Line= 3
 2305557.1237672551941.6227993212305545.22165447552038.162158107
2305645.72838417552318.523035679
#Sta/Elev= 30
       0 2779.68     7.6 2778.97    18.4 2776.71    27.8 2775.38    47.9 2770.52
    68.1 2770.01    79.4  2769.1    92.2 2767.15   113.2 2764.75     126 2761.37
   130.2 2760.83   153.4 2761.79   181.2 2760.47   202.5  2757.5   212.7 2753.37
   215.2 2752.41   219.5 2751.64     228 2751.67   236.4 2753.25   253.4 2753.45
   270.8 2754.48   283.2 2755.72   321.4 2755.02   334.2 2757.38   346.9  2758.1
   351.2 2759.89   363.9  2767.2   380.9 2775.13   386.6  2776.9   395.1 2778.49
#Mann= 4 ,-1,0
       0      .1       0   212.7    .045       0   236.4      .1       0
  247.27     .08       0
Bank Sta=212.7,236.4
XS Rating Curve= 0 ,0
Exp/Cntr(USF)=0,0
Exp/Cntr=0.3,0.1

Type RM Length L Ch R = 1 ,9721    ,272.6,260,252.8
XS GIS Cut Line= 4
2305387.84927508551962.7821108362305401.07384478552024.937588411
2305353.46539387552367.453943557 2305382.5594472552412.417480526
#Sta/Elev= 30
       0 2776.54      27 2775.81    47.4 2773.21    64.6 2772.76    71.9 2771.61
    75.9 2769.01    89.4 2757.79  101.44 2751.09   108.2 2750.14   124.4 2751.08
   144.6 2752.47   156.7 2754.72   205.1 2755.59   253.6 2753.42   277.8 2754.08
   289.9 2753.05   306.1 2753.96   339.5 2753.81   346.5 2753.24   354.6  2750.5
   358.8 2750.74   374.8 2752.46   386.9 2757.34   390.9 2757.28   394.9 2755.62
     399 2755.38   407.1 2756.74   415.5 2761.03   435.7 2773.81   462.9 2777.62
#Mann= 6 ,-1,0
       0      .1       0  101.44    .045       0   124.4      .1       0
  343.55     .08       0  419.36      .1       0  429.36     .08       0
Bank Sta=101.44,124.4
XS Rating Curve= 0 ,0
Exp/Cntr(USF)=0,0
Exp/Cntr=0.3,0.1

Type RM Length L Ch R = 1 ,9461    ,263.7,272.9,273.4
XS GIS Cut Line= 3
2305088.97399994551961.4596538662305100.87611266552034.194787198
2305271.47306175552430.931878102
#Sta/Elev= 30
       0 2786.97      20 2777.23    32.1 2774.27    44.3 2769.14    60.5 2764.32
      77 2756.56    98.7 2750.08     151 2750.74   157.1  2749.9     164 2748.34
   168.4 2748.17   177.1 2748.21   190.2 2749.58   213.7 2750.56   238.1 2748.36
   256.4 2749.49   312.1  2749.8   329.5 2751.31   346.9 2751.65   355.6 2750.81
   364.3 2751.96   377.4 2750.78   403.5 2749.98   442.7 2751.78     456 2754.01
   464.5 2754.35   473.2 2756.06   477.4 2757.54   486.2  2763.6   505.6 2773.19
#Mann= 5 ,-1,0
       0      .1       0   157.1    .045       0   190.2      .1       0
   243.7     .08       0   453.7      .1       0
Bank Sta=157.1,190.2
XS Rating Curve= 0 ,0
Exp/Cntr(USF)=0,0
Exp/Cntr=0.3,0.1

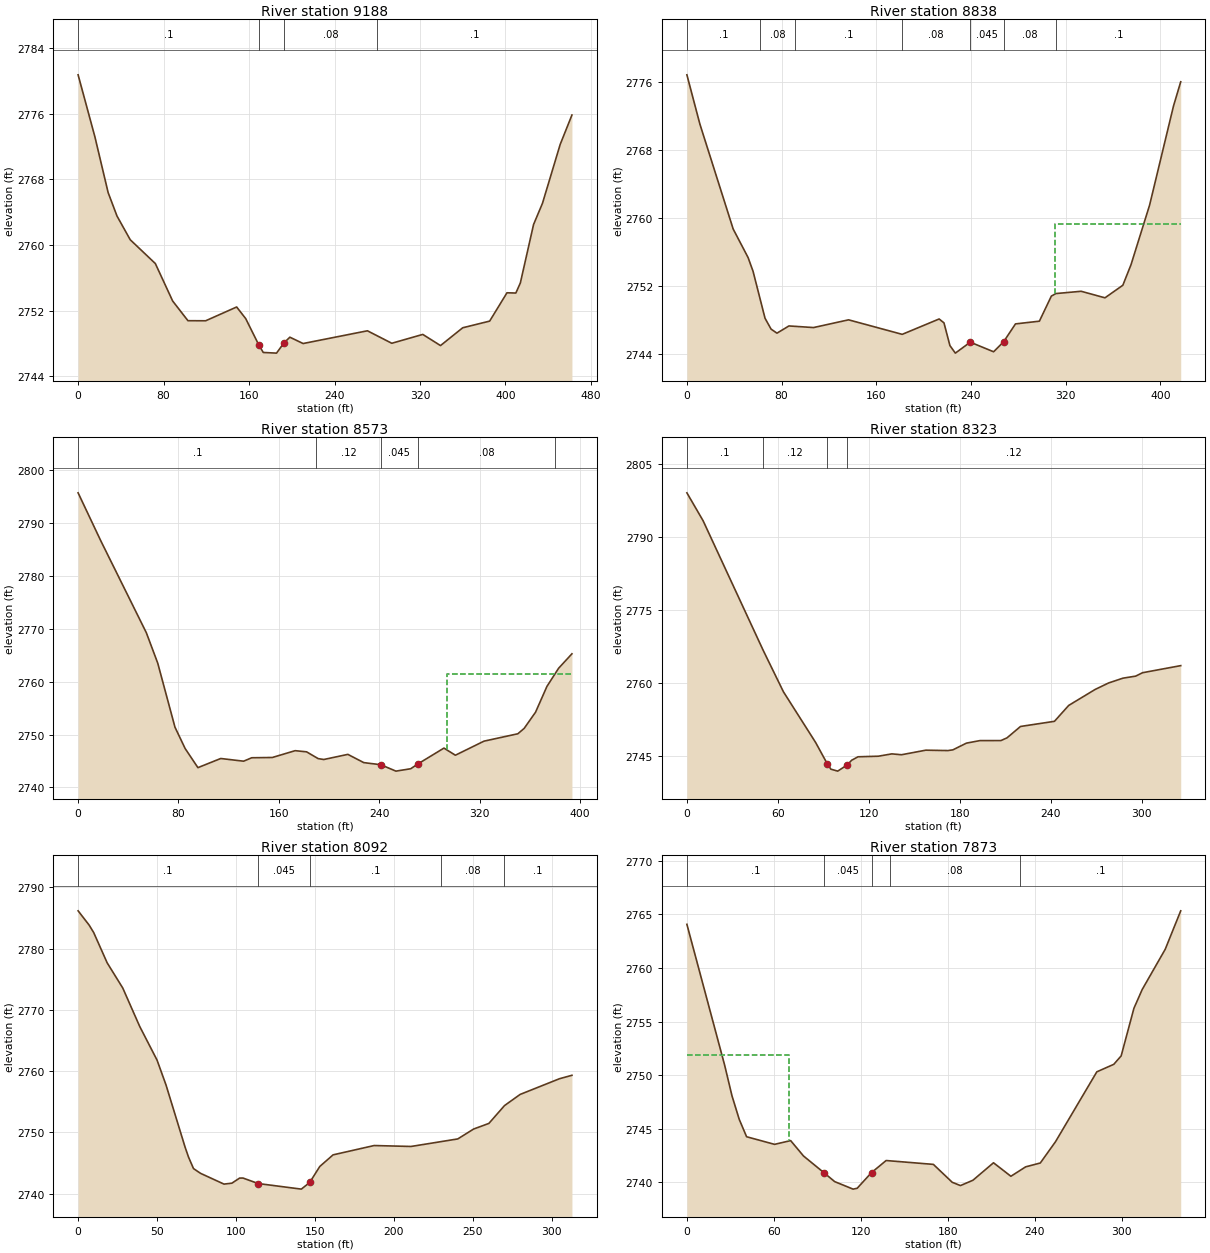
Type RM Length L Ch R = 1 ,9188    ,328.7,350.6,364
XS GIS Cut Line= 2
2304866.44204319552014.080379956 2304988.8917626552459.797358625
#Sta/Elev= 30
       0 2780.73    15.7 2773.19    28.1 2766.39    36.4 2763.53    48.8 2760.64
    72.3 2757.74    88.5 2753.18   102.8 2750.78   119.4 2750.77   148.4 2752.45
   156.9 2751.03   169.1 2747.83   173.3 2746.91   185.7 2746.83   192.7 2748.08
   198.2 2748.77   210.6    2748   270.8 2749.55   293.6 2748.03   322.6 2749.11
   339.2 2747.75     360 2749.92   385.2 2750.73   401.4 2754.18   409.7 2754.15
   413.9 2755.37   426.3  2762.5   434.6 2765.07   451.2 2772.25   462.2 2775.83
#Mann= 4 ,-1,0
       0      .1       0   169.1    .045       0   192.7     .08       0
     280      .1       0
Bank Sta=169.1,192.7
XS Rating Curve= 0 ,0
Exp/Cntr(USF)=0,0
Exp/Cntr=0.3,0.1

Type RM Length L Ch R = 1 ,8838    ,267.5,264.5,262.8
XS GIS Cut Line= 4
2304796.07681478552026.139600897  2304794.286011552077.806089042
2304594.61348992552338.5189523122304588.98005333552375.154476531
#Sta/Elev= 30
       0 2776.86      11 2771.05    39.1 2758.71    51.7 2755.35    55.9 2753.73
      66 2748.21    71.1 2746.93    76.1 2746.45    86.2  2747.3     107 2747.11
   136.6 2748.02   181.9 2746.31   213.1 2748.12   217.2 2747.66   222.2 2744.99
   226.8  2744.1   239.4 2745.39   259.1 2744.26   267.6 2745.44   277.6 2747.54
   297.8 2747.86   307.9 2750.81   311.7 2751.11   333.1 2751.38   353.2 2750.61
   368.3 2752.09   375.2 2754.51   390.9 2761.52   411.1 2773.19   417.2 2776.04
#Mann= 7 ,-1,0
       0      .1       0    61.7     .08       0    91.7      .1       0
   181.7     .08       0   239.4    .045       0   267.6     .08       0
   311.7      .1       0
#XS Ineff= 2 , 0
                          311.11         2759.32
Permanent Ineff=
       F       F
Bank Sta=239.4,267.6
XS Rating Curve= 0 ,0
Exp/Cntr(USF)=0,0
Exp/Cntr=0.3,0.1

Type RM Length L Ch R = 1 ,8573    ,247,250.5,259
XS GIS Cut Line= 2
2304568.31565282551949.4786760262304379.07206046552294.639945111
#Sta/Elev= 30
       0 2795.74    17.9 2786.75    54.4 2769.26    63.5 2763.49    77.2  2751.4
    85.3 2747.36    95.5 2743.74   113.7 2745.47   131.9 2744.96   138.4 2745.61
   154.8 2745.66     173 2746.95   182.1 2746.73   191.3 2745.45   195.8 2745.28
     215 2746.25   227.7 2744.69   241.3 2744.29   253.3 2743.08   265.1 2743.53
   270.9 2744.45   291.6 2747.44   300.7 2746.09   323.5 2748.75   350.5 2750.15
   355.5 2751.16   364.6 2754.23   373.7 2759.12     383 2762.55   393.6 2765.28
#Mann= 5 ,-1,0
       0      .1       0     190     .12       0   241.3    .045       0
   270.9     .08       0     380      .1       0
#XS Ineff= 2 , 0
                          294.11         2761.41
Permanent Ineff=
       F       F
Bank Sta=241.3,270.9
XS Rating Curve= 0 ,0
Exp/Cntr(USF)=0,0
Exp/Cntr=0.3,0.1

Type RM Length L Ch R = 1 ,8323    ,226.5,231,235.3
XS GIS Cut Line= 2
2304396.92522955551872.1149432992304251.71945428552163.716705113
#Sta/Elev= 30
       0 2799.16    10.7 2793.41    50.3 2766.77    63.7 2758.21    84.9  2747.8
   92.71 2743.35      95 2742.29    99.5 2741.89   105.8 2743.17   108.7 2744.13
   112.9 2744.84   126.3 2744.96   135.2 2745.44   141.6 2745.26   157.6  2746.2
   172.2 2746.12   175.5 2746.27   184.4 2747.65   193.3 2748.17   207.2 2748.18
   211.2 2748.74   220.1 2751.08   242.5 2752.14   251.9 2755.41   269.3 2758.69
   278.2 2760.03   287.7 2761.02   296.1 2761.44   300.6 2762.14   325.8  2763.6
#Mann= 4 ,-1,0
       0      .1       0      50     .12       0   92.71    .045       0
   105.8     .12       0
Bank Sta=92.71,105.8
XS Rating Curve= 0 ,0
Exp/Cntr(USF)=0,0
Exp/Cntr=0.3,0.1

Type RM Length L Ch R = 1 ,8092    ,211.6,218.8,223.7
XS GIS Cut Line= 2
 2304215.0017304551770.2403522782304031.82821553552023.791059704
#Sta/Elev= 30
       0 2786.15       7 2783.82     9.9 2782.59    18.4 2777.67    28.3 2773.55
      39  2767.3      50  2761.8    55.7 2757.73    67.8 2747.57      70 2745.94
    73.1  2744.1    77.6 2743.32    92.4 2741.57    97.4 2741.72   102.3 2742.55
   104.4 2742.56   114.1 2741.66   141.4 2740.75   146.7 2741.84   153.1 2744.45
   161.5 2746.34   187.5 2747.86   210.9 2747.71   240.5 2748.94   250.5 2750.55
   260.2 2751.47   270.1 2754.38     280  2756.2   304.9 2758.76   312.8 2759.32
#Mann= 5 ,-1,0
       0      .1       0   114.1    .045       0   146.7      .1       0
     230     .08       0     270      .1       0
Bank Sta=114.1,146.7
XS Rating Curve= 0 ,0
Exp/Cntr(USF)=0,0
Exp/Cntr=0.3,0.1

Type RM Length L Ch R = 1 ,7873    ,363,369.9,378
XS GIS Cut Line= 2
2304088.70841225551648.7673897862303819.73256673 551857.97082519
#Sta/Elev= 30
       0 2764.08      26 2750.96    31.1 2748.08    36.1 2745.88    41.2 2744.25
    60.5 2743.54    71.6 2743.89    80.5 2742.45    94.7 2740.88     102 2740.06
   114.7 2739.36   117.5 2739.44   127.4  2740.9   137.5 2742.03   170.1 2741.67
   183.1    2740   188.8 2739.69   197.4 2740.19   211.6 2741.82   223.6 2740.56
   233.8 2741.44   243.9  2741.8   254.4 2743.79   282.9 2750.31   294.6 2751.01
   299.7  2751.8   308.5 2756.24   314.2 2757.99   330.1 2761.75   340.8 2765.34
#Mann= 5 ,-1,0
       0      .1       0    94.7    .045       0   127.4      .1       0
     140     .08       0     230      .1       0
#XS Ineff= 2 , 0
           70.68 2751.91
Permanent Ineff=
       F       F
Bank Sta=94.7,127.4
XS Rating Curve= 0 ,0
Exp/Cntr(USF)=0,0
Exp/Cntr=0.3,0.1