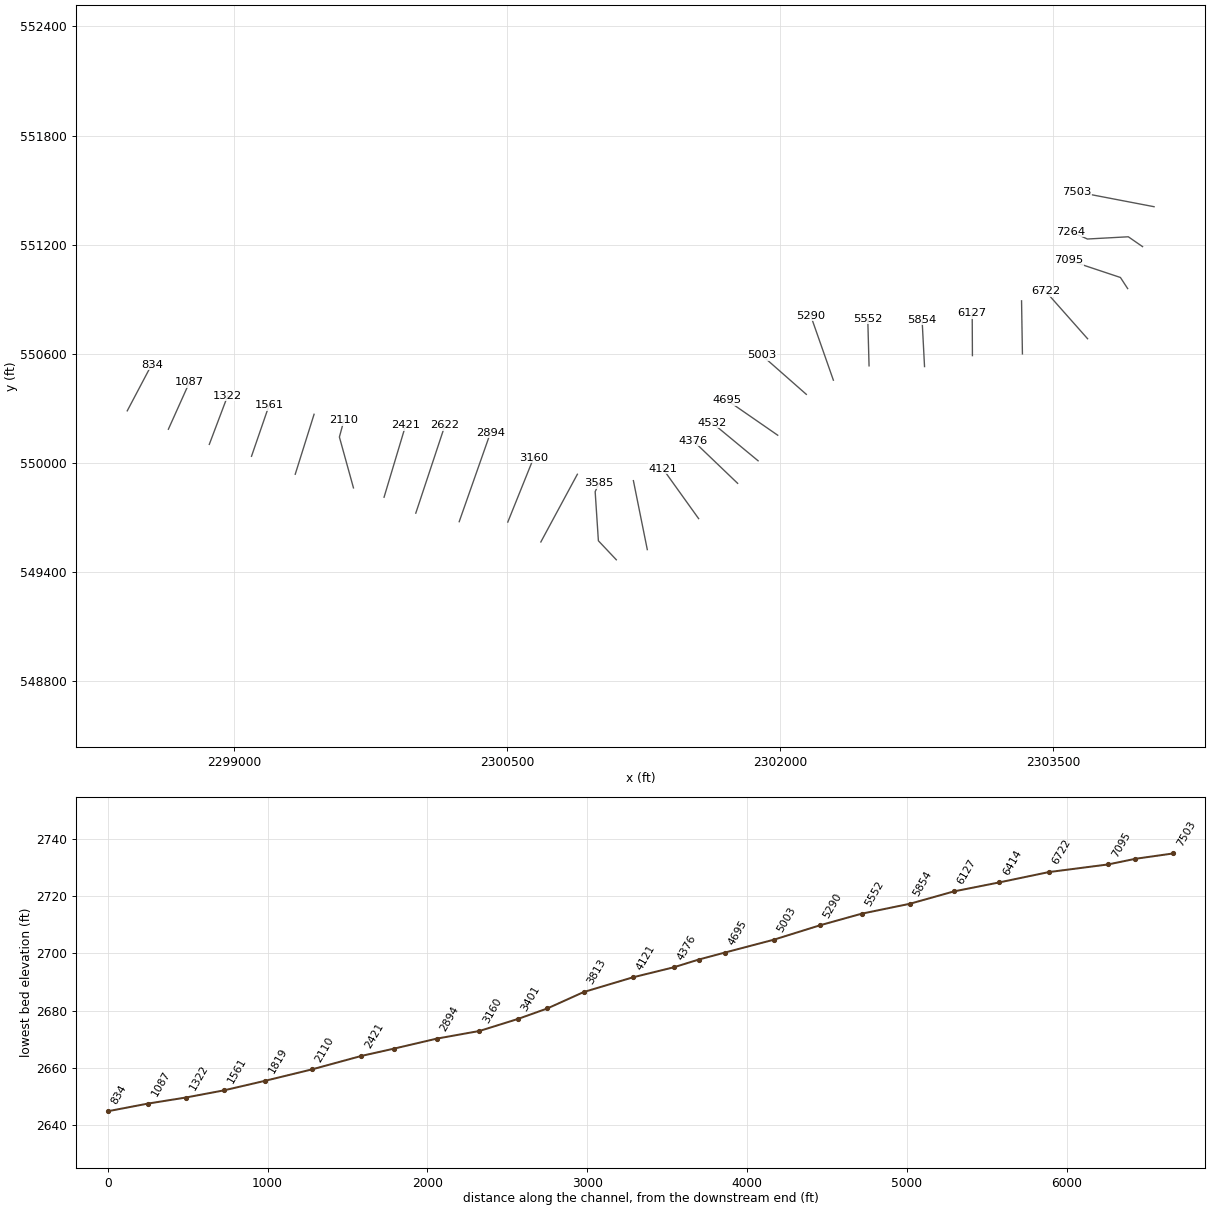
HEC-RAS study BRSHRN.prj: BRSHRN

--- BRSHRN.g01 (geometry) --- (continued)

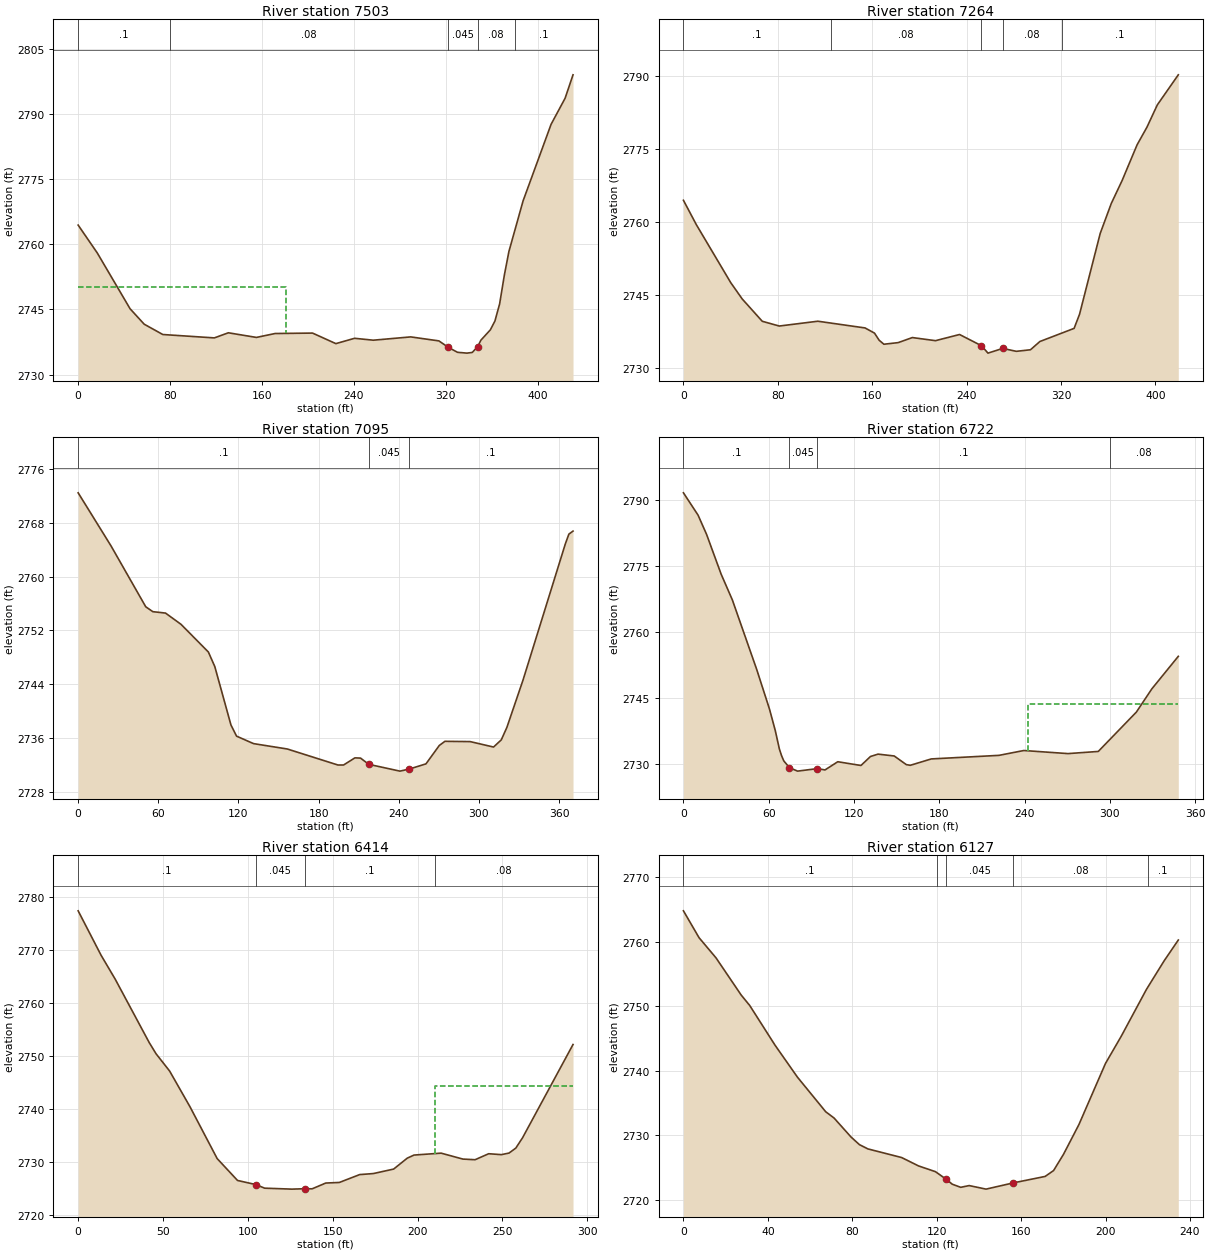
Type RM Length L Ch R = 1 ,7503    ,235,238.8,244.1
XS GIS Cut Line= 2
2304056.60461779551408.5400099042303633.40261816551489.700830847
#Sta/Elev= 30
       0 2764.44    16.7    2758    45.2 2745.16    57.5  2741.6    73.7 2739.22
   118.6 2738.44   130.8 2739.62   155.2 2738.55   171.5 2739.45   204.1 2739.55
   224.4 2737.12   240.7 2738.35     257 2737.91   289.6 2738.67   314.1 2737.75
   322.42736.252   330.3 2735.12   338.5 2734.93   343.2 2735.09   347.92736.444
   350.7 2737.92   358.9 2740.29   362.9 2742.33     367 2746.28   371.1  2752.9
   375.1 2758.38   387.4 2770.01   411.8 2787.67     424 2793.68   430.9 2799.08
#Mann= 5 ,-1,0
       0      .1       0      80     .08       0   322.4    .045       0
   347.9     .08       0     380      .1       0
#XS Ineff= 2 , 0
          180.68 2750.15
Permanent Ineff=
       F       F
Bank Sta=322.4,347.9
XS Rating Curve= 0 ,0
Exp/Cntr(USF)=0,0
Exp/Cntr=0.3,0.1

Type RM Length L Ch R = 1 ,7264    ,176.7,169.4,164.7
XS GIS Cut Line= 4
2303993.14959143551189.1748583222303914.90879955551243.220731081
 2303689.9272049551230.9237749262303599.99485174 551272.24603045
#Sta/Elev= 30
       0 2764.47    10.9 2759.47    40.1 2747.53    49.8 2744.18    66.8 2739.59
    81.2 2738.61   113.9  2739.6   153.9 2738.22   161.9 2737.16   165.9 2735.68
   169.9 2734.87     182  2735.2     194 2736.24   213.6  2735.6     234 2736.87
   252.6 2734.56   258.1 2733.04   270.6 2734.01   282.1 2733.41   294.1 2733.73
   302.1 2735.43   331.1 2738.13   335.7 2741.03   353.2 2757.64   362.6 2763.82
   371.7 2768.49   384.5 2775.89   392.8 2779.49   401.6 2784.08   419.4 2790.27
#Mann= 5 ,-1,0
       0      .1       0  125.09     .08       0   252.6    .045       0
   270.6     .08       0  320.41      .1       0
Bank Sta=252.6,270.6
XS Rating Curve= 0 ,0
Exp/Cntr(USF)=0,0
Exp/Cntr=0.3,0.1

Type RM Length L Ch R = 1 ,7095    ,381.5,372.7,367.8
XS GIS Cut Line= 3
2303911.37681137550958.3826035652303871.60364029551019.411519721
2303589.22173108551113.502243631
#Sta/Elev= 30
       0 2772.46    24.6 2764.57    50.6 2755.52    55.9 2754.79    65.4 2754.58
      77 2752.91    97.5 2748.79   102.3 2746.63   114.4 2737.94   118.6 2736.28
   131.3 2735.17   156.6 2734.37   194.5 2731.99   198.7 2731.99   207.2 2733.05
   211.4 2733.02   217.6 2732.09   240.9 2731.08   247.92731.385   260.4 2732.16
   270.4  2734.9   274.6 2735.51   293.5 2735.47     311 2734.66   316.8 2735.73
     321 2737.59   333.1 2744.64   364.7 2764.84   367.4 2766.32   370.5 2766.77
#Mann= 3 ,-1,0
       0      .1       0   217.6    .045       0   247.9      .1       0
Bank Sta=217.6,247.9
XS Rating Curve= 0 ,0
Exp/Cntr(USF)=0,0
Exp/Cntr=0.3,0.1

Type RM Length L Ch R = 1 ,6722    ,322,308.3,301.3
XS GIS Cut Line= 2
2303690.98193839 550682.645762912303460.08095149550943.302031634
#Sta/Elev= 30
       0 2791.59    10.3 2786.52    16.3 2782.14    26.5 2773.14    34.4 2767.29
    51.5 2751.53    60.5 2742.53    64.6 2737.63    67.5 2733.42      69 2731.94
    70.6 2730.72    74.6 2729.17    80.3 2728.39    94.2 2728.96    99.6 2728.66
   108.6 2730.52   124.9 2729.67   131.6 2731.71   136.9 2732.25   148.3 2731.83
   156.8 2729.87   159.6 2729.71   174.4 2731.16     222 2731.97   239.5 2733.07
   270.6 2732.37   291.9 2732.86   318.7  2741.8   329.6 2747.08   348.2 2754.46
#Mann= 4 ,-1,0
       0      .1       0    74.6    .045       0    94.2      .1       0
     300     .08       0
#XS Ineff= 2 , 0
                          242.58         2743.72
Permanent Ineff=
       F       F
Bank Sta=74.6,94.2
XS Rating Curve= 0 ,0
Exp/Cntr(USF)=0,0
Exp/Cntr=0.3,0.1

Type RM Length L Ch R = 1 ,6414    ,286.2,286.5,285.5
XS GIS Cut Line= 2
2303332.72834531550599.3309738212303327.96750022550890.932735635
#Sta/Elev= 30
       0 2777.41    13.5 2769.02    21.9 2764.45    41.9 2752.49    45.9 2750.39
    53.9 2747.12    65.9 2740.37    81.9 2730.58    93.9 2726.44   104.7 2725.66
   109.9 2724.98   125.9  2724.8   133.42724.874   137.9 2724.86   145.9 2725.95
   153.9 2726.06   165.9 2727.55   173.9 2727.74   185.9 2728.59   193.9 2730.65
   197.9 2731.24   213.9  2731.6   226.7 2730.48   233.9 2730.36   241.9 2731.49
   249.4 2731.32   253.9 2731.62   257.9 2732.56   261.9 2734.53   291.6 2752.14
#Mann= 4 ,-1,0
       0      .1       0   104.7    .045       0   133.4      .1       0
     210     .08       0
#XS Ineff= 2 , 0
                          210.33         2744.27
Permanent Ineff=
       F       F
Bank Sta=104.7,133.4
XS Rating Curve= 0 ,0
Exp/Cntr(USF)=0,0
Exp/Cntr=0.3,0.1

Type RM Length L Ch R = 1 ,6127    ,271.9,273.2,274
XS GIS Cut Line= 2
2303057.78954131550589.8092836392303056.59933004550824.280904363
#Sta/Elev= 30
       0 2764.79     7.4 2760.62    15.4 2757.51    27.4 2751.71    31.4 2750.11
    43.4 2743.95      54    2739    67.4 2733.63    71.4 2732.64    79.4 2729.71
    83.4 2728.52    87.4 2727.86   103.4 2726.52   111.4 2725.22   119.4 2724.33
   124.4 2723.18   127.4 2722.38   131.4  2721.9   135.4 2722.17   143.4 2721.62
   156.2 2722.58   171.4 2723.59   175.4  2724.5   180.1 2727.02   187.4 2731.63
     200 2741.12   207.4  2745.3   219.4  2752.6   227.8 2757.04   234.5 2760.26
#Mann= 5 ,-1,0
       0      .1       0     120     .08       0   124.4    .045       0
   156.2     .08       0     220      .1       0
Bank Sta=124.4,156.2
XS Rating Curve= 0 ,0
Exp/Cntr(USF)=0,0
Exp/Cntr=0.3,0.1

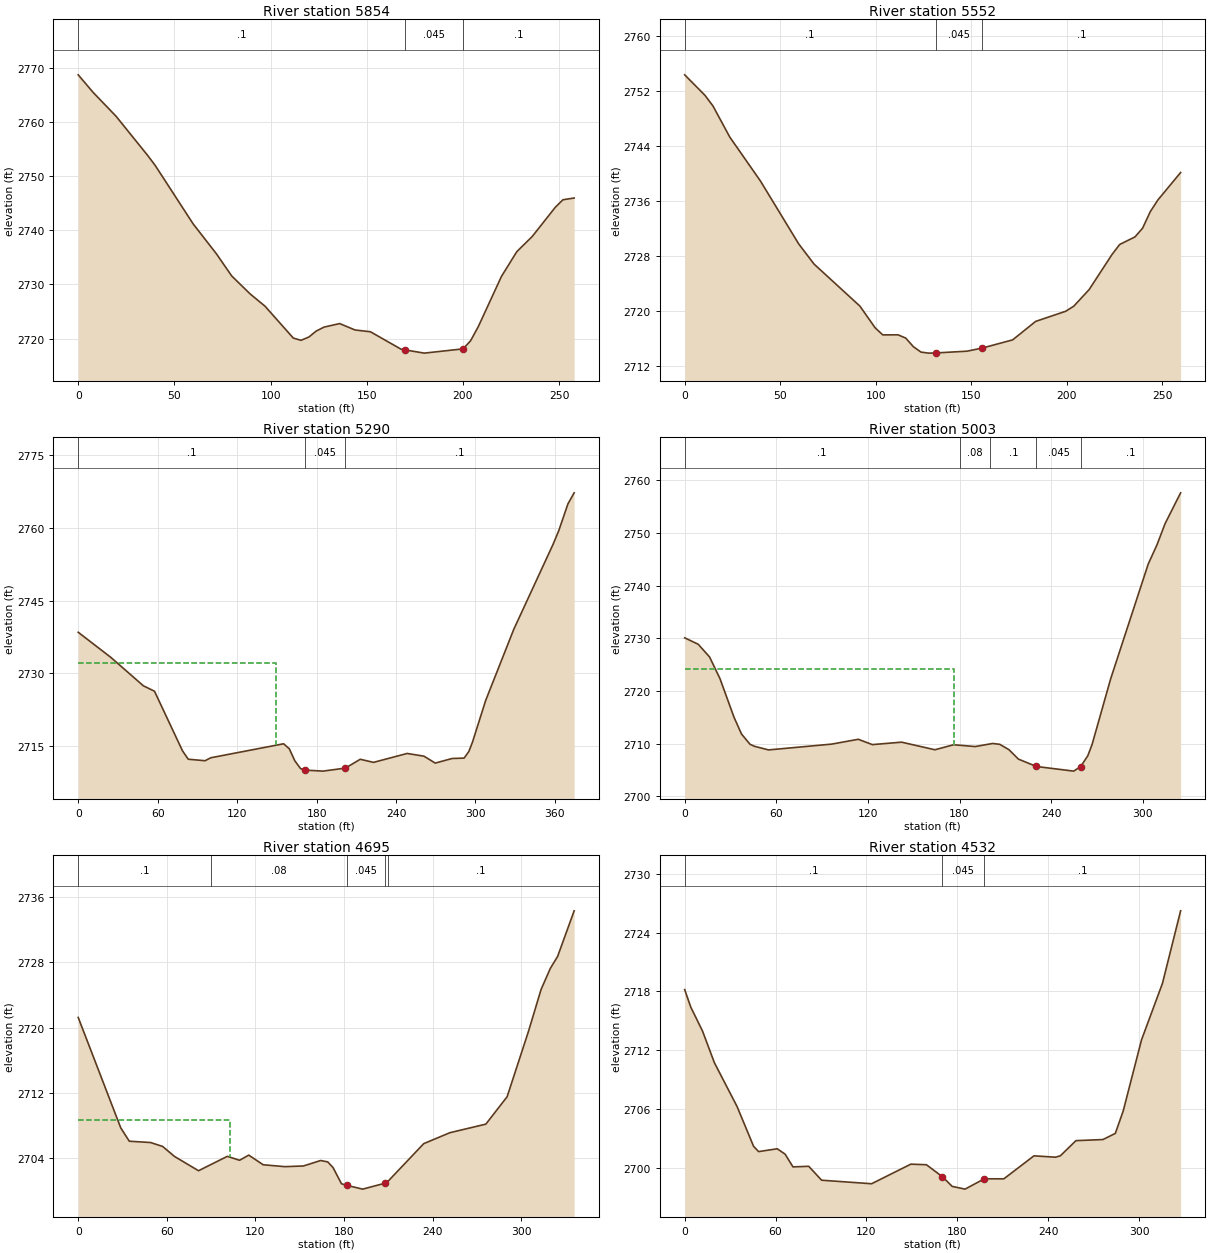
Type RM Length L Ch R = 1 ,5854    ,302.3,301.9,302
XS GIS Cut Line= 2
2302794.50539663  550529.50537712302781.02339663 550786.99527206
#Sta/Elev= 30
       0 2768.66     7.7 2765.44    19.7 2761.01    36.2 2753.75      40 2751.96
    59.8 2741.14    71.8 2735.67    79.8 2731.56    89.4 2728.24    97.1 2725.99
   111.8 2720.11   115.8 2719.69   119.9  2720.3   123.8 2721.42   127.8 2722.13
   135.9 2722.78   143.9  2721.6   151.9 2721.27   167.9 2718.04   169.72717.939
   179.9 2717.33   200.1 2718.12     204 2719.63     208 2722.24     220 2731.47
     228 2736.05     236 2738.84     248 2744.23     252 2745.62   257.8 2745.94
#Mann= 3 ,-1,0
       0      .1       0   169.7    .045       0   200.1      .1       0
Bank Sta=169.7,200.1
XS Rating Curve= 0 ,0
Exp/Cntr=0.3,0.1

Type RM Length L Ch R = 1 ,5552    ,254.7,262.3,266.4
XS GIS Cut Line= 2
2302489.46449409 550533.539341472302482.32322646 550793.00539892
#Sta/Elev= 30
       0 2754.31    10.6 2751.34    14.8 2749.79    23.6 2745.27    39.7 2738.86
    59.7 2729.73    67.7 2726.81    91.7  2720.7    99.7 2717.54   103.7 2716.51
   111.7 2716.52   115.7 2716.05   119.7  2714.8   123.7 2714.01   127.7 2713.86
   131.32713.885   147.7 2714.14   155.7 2714.59   171.7 2715.79   183.7 2718.47
   199.5 2719.95   203.7 2720.69   211.7 2723.09   223.7  2728.2   227.7 2729.65
   235.7 2730.75   239.7 2732.02   243.7 2734.41   247.7 2736.12   259.6 2740.11
#Mann= 3 ,-1,0
       0      .1       0   131.3    .045       0   155.7      .1       0
Bank Sta=131.3,155.7
XS Rating Curve= 0 ,0
Exp/Cntr(USF)=0,0
Exp/Cntr=0.3,0.1

Type RM Length L Ch R = 1 ,5290    ,277.6,287.3,297.3
XS GIS Cut Line= 2
2302293.25514037550454.7970432692302169.24766146550808.122197816
#Sta/Elev= 30
       0 2738.47    24.7 2733.27    49.2 2727.41    57.6 2726.29    78.8 2713.95
    83.1 2712.24    95.8 2711.93   100.1 2712.54   155.1 2715.43   159.4  2714.4
   163.6  2711.9   167.9 2710.31     1712710.001   184.8 2709.78   201.8 2710.41
     213 2712.23     223 2711.59   248.4 2713.43   261.1 2712.87   269.6 2711.44
   282.3 2712.39   291.4 2712.47     295 2713.85   297.7 2715.75   307.7 2724.39
   328.9 2739.07   358.6 2756.65   362.9 2759.48   369.8 2764.99   374.5 2767.28
#Mann= 3 ,-1,0
       0      .1       0     171    .045       0   201.8      .1       0
#XS Ineff= 2 , 0
          149.57 2732.15
Permanent Ineff=
       F       F
Bank Sta=171,201.8
XS Rating Curve= 0 ,0
Exp/Cntr=0.3,0.1

Type RM Length L Ch R = 1 ,5003    ,305.6,307.8,310.7
XS GIS Cut Line= 2
2302144.43902964 550376.906940682301900.51918856550591.438849094
#Sta/Elev= 30
       0  2730.1     8.9 2728.87    16.3 2726.46    23.1 2722.36    32.3 2715.02
    37.2 2711.83    42.8 2709.87    45.7 2709.49    54.9  2708.8    96.2  2709.9
   113.7 2710.82   122.9 2709.81   142.1 2710.27   163.9 2708.83   176.1 2709.78
   190.3 2709.44   201.6 2710.02   206.3 2709.87   212.4 2708.84   218.6 2707.05
   230.4 2705.65   254.8 2704.77  259.32 2705.64     264 2707.68   266.8 2709.82
     279 2722.32   303.6 2744.13   309.3 2747.75   314.6 2751.78   324.8 2757.65
#Mann= 5 ,-1,0
       0      .1       0     180     .08       0     200      .1       0
   230.4    .045       0  259.32      .1       0
#XS Ineff= 2 , 0
          176.23 2724.12
Permanent Ineff=
       F       F
Bank Sta=230.4,259.32
XS Rating Curve= 0 ,0
Exp/Cntr(USF)=0,0
Exp/Cntr=0.3,0.1

Type RM Length L Ch R = 1 ,4695    ,164.4,162.6,161.1
XS GIS Cut Line= 2
2301987.21358991550152.0892558352301710.96702291550343.110818122
#Sta/Elev= 30
       0 2721.25    28.8 2707.75    34.6 2706.11      49 2705.95    57.2 2705.47
    65.2 2704.25    81.5  2702.5     101 2704.26   109.3 2703.78   115.5 2704.41
   125.3 2703.23   139.9    2703   152.5 2703.08   164.2 2703.75     169 2703.58
   172.6 2702.89   178.3 2700.91   182.12700.703   192.7 2700.25   207.9 2700.98
     210 2701.24     234 2705.81   251.7 2707.15   276.1  2708.2   290.5 2711.55
   304.9 2719.51   313.5 2724.67   319.8 2727.26   324.7 2728.71   335.9 2734.29
#Mann= 5 ,-1,0
       0      .1       0      90     .08       0   182.1    .045       0
   207.9     .08       0     210      .1       0
#XS Ineff= 2 , 0
          102.55 2708.76
Permanent Ineff=
       F       F
Bank Sta=182.1,207.9
XS Rating Curve= 0 ,0
Exp/Cntr(USF)=0,0
Exp/Cntr=0.3,0.1

Type RM Length L Ch R = 1 ,4532    ,157.3,155.8,154.1
XS GIS Cut Line= 2
2301879.26908394550011.5994237252301626.97820175550220.224576309
#Sta/Elev= 30
       0 2718.19       4 2716.41    11.8 2713.95    19.6 2710.73    34.6 2706.25
    45.5 2702.19    48.8 2701.65    61.1 2701.94    66.3 2701.39    71.5 2700.09
    81.9 2700.15    90.4 2698.73   123.4 2698.37   149.3 2700.37   159.6 2700.31
   170.1 2699.09   176.6  2698.1   185.1 2697.82   197.82698.875   210.7 2698.87
   230.6 2701.22   244.8 2701.08     248 2701.22   258.3 2702.77   276.1 2702.88
   284.3 2703.51   289.5  2705.8   301.6 2713.06   315.4 2718.82   327.4 2726.23
#Mann= 3 ,-1,0
       0      .1       0   170.1    .045       0   197.8      .1       0
Bank Sta=170.1,197.8
XS Rating Curve= 0 ,0
Exp/Cntr(USF)=0,0
Exp/Cntr=0.3,0.1

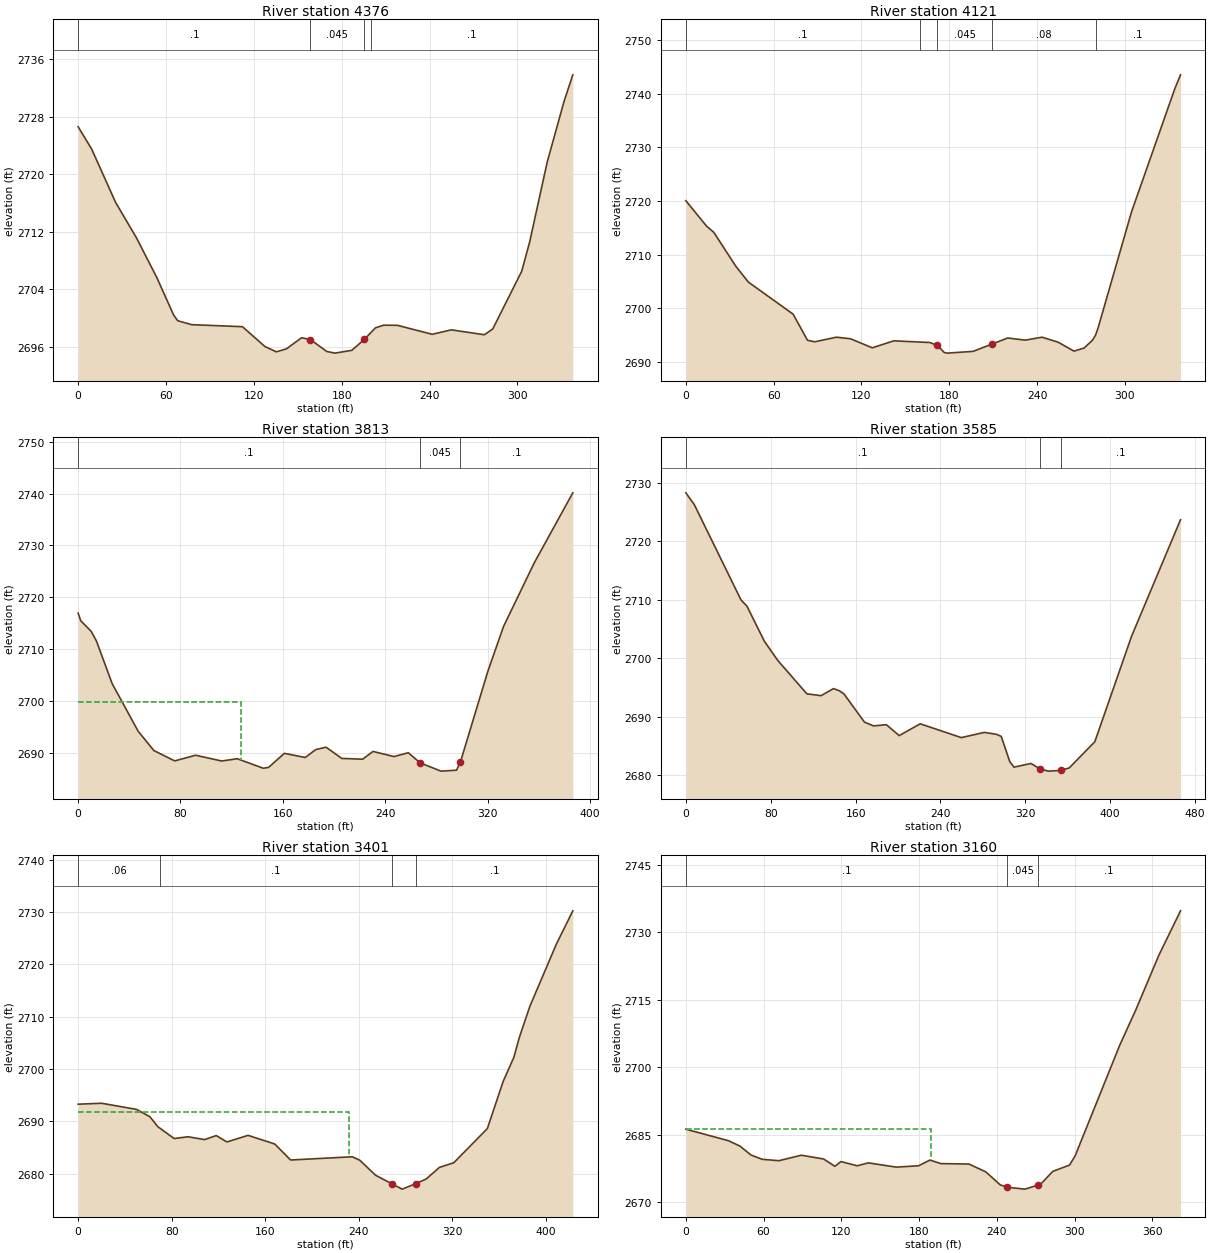
Type RM Length L Ch R = 1 ,4376    ,259.9,255.3,251.2
XS GIS Cut Line= 2
2301766.80409496549887.5978619012301522.88425389550121.231926543
#Sta/Elev= 30
       0 2726.63     9.2 2723.54    25.6 2716.09    39.8 2711.18    53.9 2705.57
    65.2 2700.42      68 2699.63    77.5 2699.08   112.2  2698.8   127.5 2696.05
   135.3  2695.3   142.1  2695.7   152.6 2697.26   158.6 2697.01   169.8 2695.35
   175.3 2695.12   186.9 2695.51   195.4 2697.03     203 2698.64   208.6 2699.01
     218 2698.99   241.8 2697.74   254.8 2698.36   277.4 2697.68   283.1 2698.48
   302.9 2706.52   308.3 2710.57   320.3 2721.71   331.9 2730.23   337.8 2733.86
#Mann= 4 ,-1,0
       0      .1       0   158.6    .045       0   195.4     .08       0
     200      .1       0
Bank Sta=158.6,195.4
XS Rating Curve= 0 ,0
Exp/Cntr(USF)=0,0
Exp/Cntr=0.3,0.1

Type RM Length L Ch R = 1 ,4121    ,309.7,308.6,290
XS GIS Cut Line= 2
2301552.27218655549693.6375063492301355.37303773549968.414676714
#Sta/Elev= 30
       0 2720.03    14.2 2715.28    19.1 2714.14    34.1 2707.83    42.7 2704.87
    73.3 2698.88    83.1 2694.02      88 2693.73   102.9 2694.59   112.6 2694.29
   127.4 2692.61   142.1 2693.91   166.7  2693.6   171.8 2693.08   176.6 2691.73
   178.7 2691.62   196.3 2691.95     209 2693.29   219.9 2694.44   231.9 2694.04
   243.4 2694.59   254.3 2693.67   265.2 2691.99   272.1 2692.57   277.8 2694.02
   279.9 2694.94   281.7 2696.34   304.5 2717.94   334.1 2740.92     338  2743.5
#Mann= 5 ,-1,0
       0      .1       0     160     .08       0   171.8    .045       0
     209     .08       0     280      .1       0
Bank Sta=171.8,209
XS Rating Curve= 0 ,0
Exp/Cntr(USF)=0,0
Exp/Cntr=0.3,0.1

Type RM Length L Ch R = 1 ,3813    ,230.9,228,226
XS GIS Cut Line= 2
2301270.14803302549523.187496924 2301193.7394081 549902.29182823
#Sta/Elev= 30
       0 2716.96       2 2715.49    10.2 2713.44    14.3 2711.58    26.5  2703.4
    46.9 2694.17    59.2 2690.44    75.5 2688.44    91.8 2689.54   112.2 2688.42
   124.4 2688.86   144.8 2687.02   148.9  2687.2   161.2  2689.9   177.5  2689.1
   185.7 2690.62   193.8 2691.09   206.1 2688.92   222.4 2688.77   230.5 2690.27
   246.9 2689.28   258.1 2690.02   267.3 2688.07   283.6 2686.47   295.8 2686.65
   298.8 2688.21   320.3 2705.75   332.5 2714.36   356.5 2726.63   386.7 2740.16
#Mann= 3 ,-1,0
       0      .1       0   267.3    .045       0   298.8      .1       0
#XS Ineff= 2 , 0
          127.58 2699.87
Permanent Ineff=
       F       F
Bank Sta=267.3,298.8
XS Rating Curve= 0 ,0
Exp/Cntr(USF)=0,0
Exp/Cntr=0.3,0.1

Type RM Length L Ch R = 1 ,3585    ,191,183.5,174
XS GIS Cut Line= 4
2301099.69802359549467.3504248712301001.24844918549571.677585812
2300983.51362442549841.7661856492301005.65663908549889.067258534
#Sta/Elev= 30
       0 2728.29       8 2726.26      52 2709.98    57.6 2708.92      74 2702.93
    86.7 2699.63   114.1 2693.93   127.5 2693.62   139.2 2694.83   144.9 2694.44
     149 2693.93   168.4 2689.09     177 2688.45     189 2688.66   201.1 2686.79
   220.9 2688.81   259.7 2686.45   281.3 2687.34   292.6 2687.02   297.3 2686.66
   305.3 2682.36   309.3  2681.4   325.3 2682.03   333.4 2681.15   341.4 2680.72
   353.52680.842   361.4 2681.27   385.5 2685.74   420.2  2703.8   466.3 2723.69
#Mann= 3 ,-1,0
       0      .1       0   333.4    .045       0   353.5      .1       0
Bank Sta=333.4,353.5
XS Rating Curve= 0 ,0
Exp/Cntr(USF)=0,0
Exp/Cntr=0.3,0.1

Type RM Length L Ch R = 1 ,3401    ,239.6,241.3,243.1
XS GIS Cut Line= 2
2300684.86329394549565.2656488622300885.68083378549937.512795882
#Sta/Elev= 30
       0 2693.28    20.1 2693.46    49.9 2692.29    61.4 2690.88    68.1 2688.99
    82.1 2686.72    93.9 2687.06   108.1 2686.52   118.1 2687.29   127.2 2686.07
   145.3 2687.33   168.1 2685.68   181.7 2682.62   234.4 2683.24   240.8 2682.58
   254.4  2679.7   268.1  2678.1   268.1 2678.09   277.1 2677.06   288.72678.103
   297.6 2678.99     309 2681.22   321.2  2682.1   349.9 2688.62   363.5 2697.67
   372.6 2702.24   377.1 2705.92   386.2 2711.94   408.9 2723.84     423 2730.21
#Mann= 4 ,-1,0
       0     .06       0      70      .1       0   268.1    .045       0
   288.7      .1       0
#XS Ineff= 2 , 0
           231.3 2691.81
Permanent Ineff=
       F       F
Bank Sta=268.1,288.7
XS Rating Curve= 0 ,0
Exp/Cntr(USF)=0,0
Exp/Cntr=0.3,0.1

Type RM Length L Ch R = 1 ,3160    ,265.1,265.5,267
XS GIS Cut Line= 2
2300503.12299061 549674.535350122300645.65446401550028.659938666
#Sta/Elev= 30
       0  2686.2      33 2683.62    41.7 2682.44    50.3 2680.44    58.9 2679.49
    71.8 2679.18    89.1  2680.4   106.3 2679.56     115 2677.94   119.7 2678.98
   132.2 2678.05   140.8 2678.69   162.4 2677.75   179.6 2678.05   188.3 2679.32
   196.9 2678.53   218.4 2678.44   231.4  2676.7   242.6  2673.8   248.12673.267
   261.6 2672.85   271.42673.706   274.5 2674.16   283.1  2676.8   296.1 2678.21
   300.4 2680.27   334.8  2704.9   347.2 2712.76     365 2724.94   381.7 2734.81
#Mann= 3 ,-1,0
       0      .1       0   248.1    .045       0   271.4      .1       0
#XS Ineff= 2 , 0
          189.29 2686.33
Permanent Ineff=
       F       F
Bank Sta=248.1,271.4
XS Rating Curve= 0 ,0
Exp/Cntr(USF)=0,0
Exp/Cntr=0.3,0.1

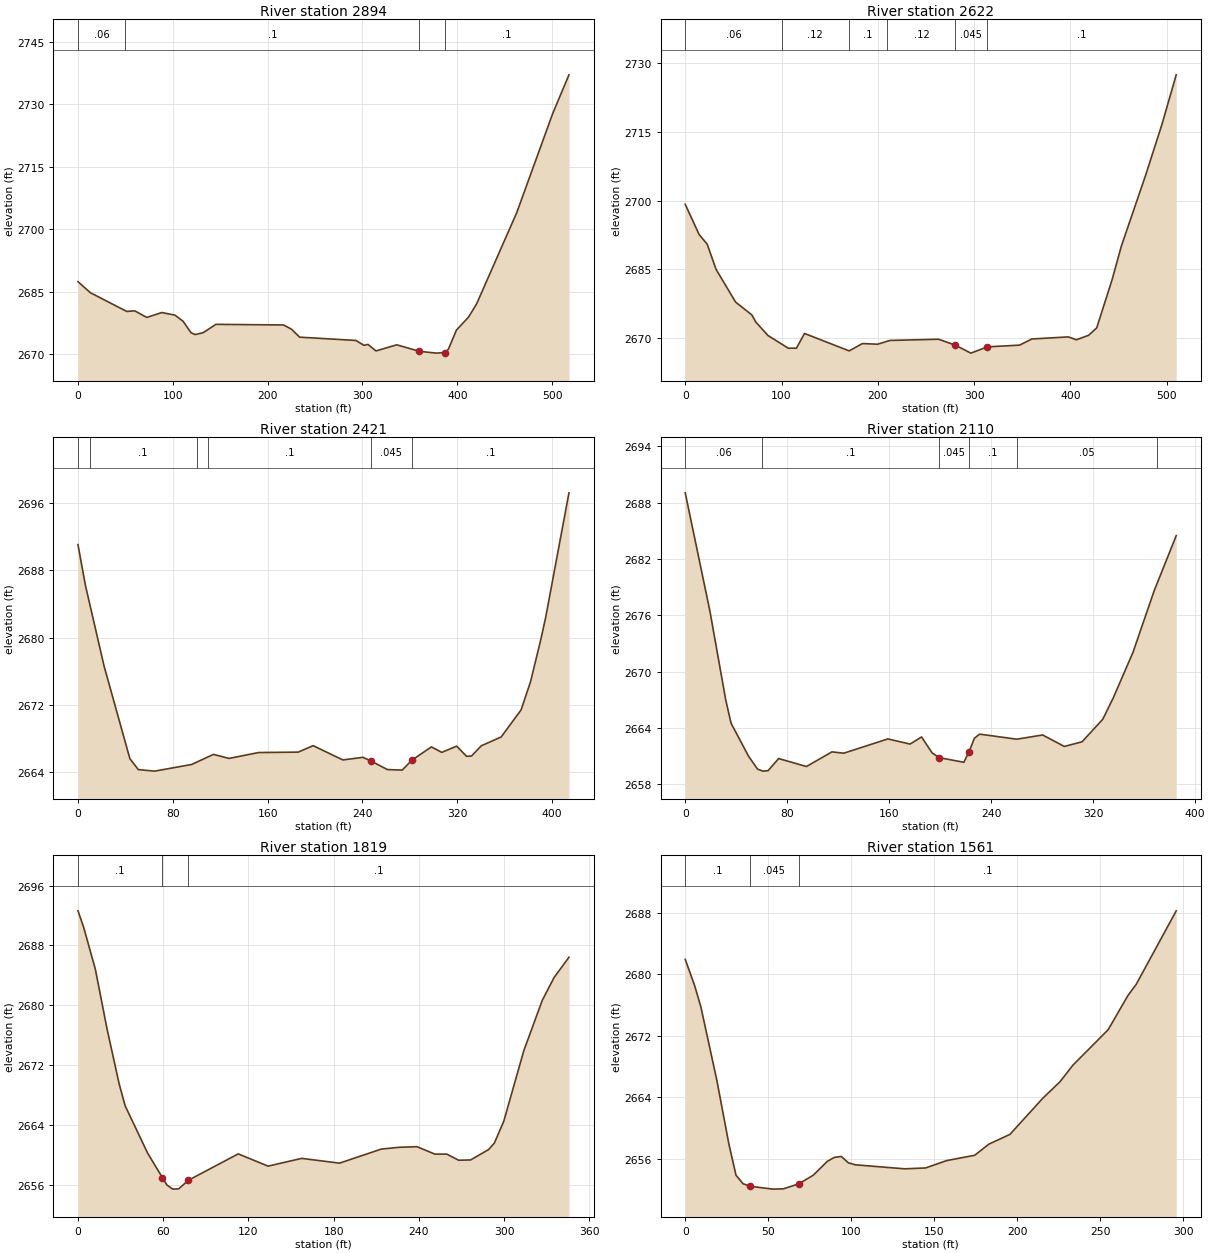
Type RM Length L Ch R = 1 ,2894    ,274.8,272.2,272.5
XS GIS Cut Line= 2
2300235.92001211549676.6963773742300407.67349702550165.190055228
#Sta/Elev= 30
       0 2687.38    13.1 2684.72    51.4 2680.22    59.9 2680.36    72.6 2678.77
    88.4 2679.95   102.3 2679.33   110.8 2677.87   119.2  2675.1   123.5 2674.65
     132  2675.1   145.5 2677.11   216.8 2676.96   225.2 2675.94   233.7 2674.03
   293.1 2673.24   301.6 2672.06   305.8 2672.29   314.3 2670.72   336.2 2672.19
     360 2670.63   377.9 2670.19   386.7 2670.34   390.6 2671.11   399.1 2675.72
   411.8 2678.83   420.3 2681.97   462.7 2703.95   500.8 2727.89   517.8 2737.11
#Mann= 4 ,-1,0
       0     .06       0      50      .1       0     360    .045       0
   386.7      .1       0
Bank Sta=360,386.7
XS Rating Curve= 0 ,0
Exp/Cntr(USF)=0,0
Exp/Cntr=0.3,0.1

Type RM Length L Ch R = 1 ,2622    ,200.4,201.5,201.9
XS GIS Cut Line= 2
2299997.24958504549723.5382368952300157.85024625 550207.57078527
#Sta/Elev= 30
       0  2699.2    14.4 2692.59    22.8 2690.47    32.1 2684.94    52.3 2677.81
    69.2    2675    73.4 2673.41      86 2670.49   107.1 2667.71   115.5 2667.71
   123.9 2670.94   170.3 2667.13     184 2668.73   199.8 2668.59   212.5 2669.41
   263.1 2669.68   280.62668.377   296.7 2666.64   313.9 2668.01   347.3 2668.39
     360 2669.73   397.9 2670.19   406.3 2669.56     419 2670.54   427.4 2672.15
   443.5 2682.78     453 2690.04     478 2705.41   494.8 2716.41     510 2727.51
#Mann= 6 ,-1,0
       0     .06       0     100     .12       0     170      .1       0
     210     .12       0   280.6    .045       0   313.9      .1       0
Bank Sta=280.6,313.9
XS Rating Curve= 0 ,0
Exp/Cntr(USF)=0,0
Exp/Cntr=0.3,0.1

Type RM Length L Ch R = 1 ,2421    ,297.2,310.2,319.2
XS GIS Cut Line= 2
2299822.79234954549811.1892369862299941.81347681550207.926327889
#Sta/Elev= 30
       0 2691.06     6.3 2686.21      22 2676.63    43.8  2665.6    50.9  2664.3
    64.7 2664.12    95.9 2664.91   114.3 2666.11   127.4 2665.63   152.4 2666.33
   185.8 2666.38   198.4 2667.15   223.4 2665.45   240.4 2665.76   246.9 2665.34
     261 2664.31   273.5 2664.24   281.9 2665.45   298.2    2667   306.9 2666.35
   319.5 2667.09   327.8 2665.88     332 2665.92   340.3 2667.14     357 2668.18
   373.8  2671.4   381.8 2674.76   390.5  2679.8   394.6 2682.44   414.2 2697.22
#Mann= 6 ,-1,0
       0     .06       0      10      .1       0     100     .12       0
     110      .1       0   246.9    .045       0   281.9      .1       0
Bank Sta=246.9,281.9
XS Rating Curve= 0 ,0
Exp/Cntr(USF)=0,0
Exp/Cntr=0.3,0.1

Type RM Length L Ch R = 1 ,2110    ,292.7,291.3,276.3
XS GIS Cut Line= 3
2299654.55101504549862.5188360982299577.18728232550142.218485184
2299602.18171904550233.864753182
#Sta/Elev= 30
       0 2689.04    19.4 2676.42    31.8 2666.97      36 2664.49    49.6 2661.01
    56.7 2659.62    60.9  2659.4      65 2659.45    73.3 2660.74    95.1 2659.89
   115.1 2661.45   124.4 2661.31     159 2662.83   176.4 2662.28   185.4 2663.04
   193.7 2661.34   199.2 2660.84   218.6 2660.34   222.7 2661.48   226.9 2662.91
     231 2663.34   260.1  2662.8   280.4 2663.25   297.4 2662.03   311.3 2662.52
   327.6 2664.93   335.8  2667.2   351.3 2672.06   367.9 2678.61   385.2 2684.48
#Mann= 6 ,-1,0
       0     .06       0      60      .1       0   199.2    .045       0
   222.7      .1       0     260     .05       0   370.2      .1       0
Bank Sta=199.2,222.7
XS Rating Curve= 0 ,0
Exp/Cntr(USF)=0,0
Exp/Cntr=0.3,0.1

Type RM Length L Ch R = 1 ,1819    ,258.1,258,257.3
XS GIS Cut Line= 2
2299334.38418268549937.5021462782299437.93256341550267.190668818
#Sta/Elev= 30
       0 2692.63     3.9  2690.5    12.2 2684.86    20.6 2676.73      29  2669.5
    33.2 2666.58      49 2660.26    59.4 2656.99    62.6    2656    66.7 2655.44
    70.9 2655.48    77.7 2656.62   112.8 2660.15   133.8 2658.51   157.5 2659.55
   184.1 2658.91   213.5 2660.79   226.1 2661.03   238.6 2661.11   251.2 2660.12
   259.6 2660.12     268  2659.3   276.4 2659.34     289 2660.72   293.1  2661.6
   299.7  2664.5   313.8 2673.93   326.8 2680.66   335.1 2683.71   345.6 2686.43
#Mann= 3 ,-1,0
       0      .1       0    59.4    .045       0    77.7      .1       0
Bank Sta=59.4,77.7
XS Rating Curve= 0 ,0
Exp/Cntr(USF)=0,0
Exp/Cntr=0.3,0.1

Type RM Length L Ch R = 1 ,1561    ,239.4,238.8,238.3
XS GIS Cut Line= 2
 2299093.9615056550036.2896819132299190.36861869550315.989330999
#Sta/Elev= 30
       0 2681.95     5.6 2678.59     9.4  2675.8    19.1 2666.18    26.3 2657.95
    30.6 2653.89    34.8  2652.8    38.82652.468    52.8 2652.09    59.1 2652.13
    68.32652.768    77.1 2653.89    85.6  2655.7    89.8 2656.21      94 2656.34
    98.3 2655.51   102.5 2655.25   132.1 2654.73   144.8 2654.84   157.5  2655.8
   174.4 2656.49   182.9 2657.93   195.6  2659.2   215.5 2663.92   225.8 2666.05
   233.6 2668.21   254.8 2672.81   266.7 2677.25   271.7 2678.71   295.8 2688.26
#Mann= 3 ,-1,0
       0      .1       0    38.8    .045       0    68.3      .1       0
Bank Sta=38.8,68.3
XS Rating Curve= 0 ,0
Exp/Cntr(USF)=0,0
Exp/Cntr=0.3,0.1

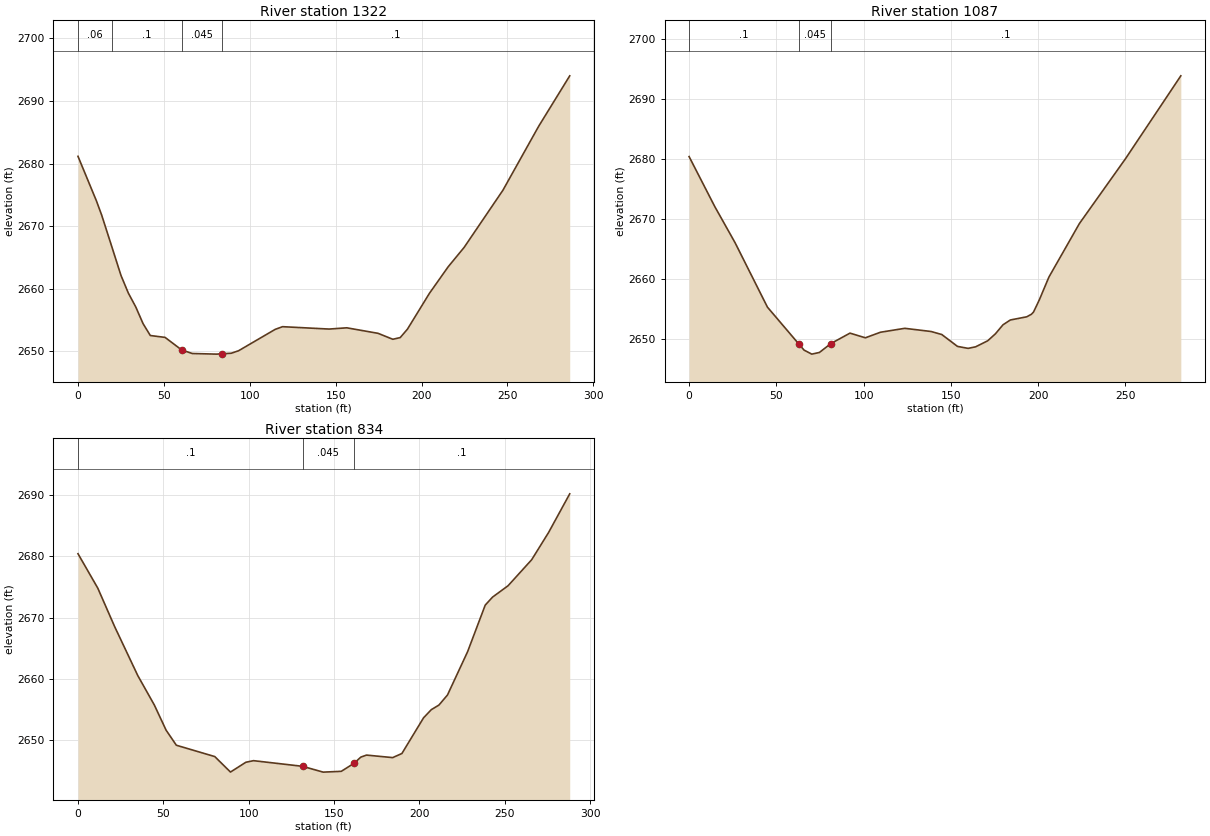
Type RM Length L Ch R = 1 ,1322    ,236.5,235.7,234.8
XS GIS Cut Line= 2
2298861.87030742550101.751301912 2298963.0382656 550369.54883827
#Sta/Elev= 30
       0 2681.15    10.7 2674.06    13.8 2671.76      20 2666.46      25 2662.16
    29.3 2659.33    33.6 2657.13    37.9 2654.44    42.1 2652.55    50.7 2652.25
    60.3 2650.26    66.5 2649.68    80.6 2649.58    83.62649.629    89.2 2649.72
    93.5 2650.12   114.8 2653.53   119.1 2653.96   146.2 2653.58   156.5 2653.78
   174.7  2652.9   183.3 2651.95   187.6 2652.22   191.8 2653.56   204.6 2659.28
   215.5 2663.51   224.8 2666.61   247.4 2675.74   268.2 2685.94   286.3    2694
#Mann= 4 ,-1,0
       0     .06       0      20      .1       0    60.3    .045       0
    83.6      .1       0
Bank Sta=60.3,83.6
XS Rating Curve= 0 ,0
Exp/Cntr(USF)=0,0
Exp/Cntr=0.3,0.1

Type RM Length L Ch R = 1 ,1087    ,252.1,252.2,253.6
XS GIS Cut Line= 2
2298636.92037688550185.0660910012298752.37087033550442.151725906
#Sta/Elev= 30
       0  2680.4    14.7 2672.08    26.4 2666.02    44.9 2655.31    63.1 2649.09
    65.9 2648.15    70.3 2647.48    74.7 2647.76    81.2 2649.23    92.2 2650.98
     101  2650.2   109.7 2651.13   123.6 2651.78   138.7 2651.25   144.8 2650.75
   153.8 2648.77   159.9 2648.44   164.2  2648.7   171.1  2649.7   175.5 2650.85
   179.9 2652.37   184.1 2653.17   193.5  2653.7   196.2 2654.13   197.4  2654.5
   200.7 2656.52   206.2 2660.32   223.7 2669.25   250.1 2680.05   281.8 2693.86
#Mann= 3 ,-1,0
       0      .1       0    63.1    .045       0    81.2      .1       0
Bank Sta=63.1,81.2
XS Rating Curve= 0 ,0
Exp/Cntr(USF)=0,0
Exp/Cntr=0.3,0.1

Type RM Length L Ch R = 1 ,834     ,268.5,265.6,260.1
XS GIS Cut Line= 2
2298410.78023506550286.2340491812298545.27410888 550540.93926154
#Sta/Elev= 30
       0 2680.44    11.6 2674.82    21.4 2668.58      35 2660.56    44.7 2655.75
    51.6 2651.64    57.6 2649.18    80.1 2647.33    89.3  2644.8    98.3  2646.4
   102.8 2646.66   131.5 2645.74   143.6 2644.79   154.2 2644.92   161.6 2646.22
   165.7 2647.25     169 2647.57   184.3 2647.16   189.7 2647.83   202.4 2653.66
   206.9 2654.98   211.4 2655.74   216.4 2657.38   228.2 2664.46   238.5 2672.05
   242.8 2673.36   251.9 2675.22   265.7 2679.46   275.6  2683.9     288 2690.22
#Mann= 3 ,-1,0
       0      .1       0   131.5    .045       0   161.6      .1       0
Bank Sta=131.5,161.6
XS Rating Curve= 0 ,0
Exp/Cntr(USF)=0,0
Exp/Cntr=0.3,0.1