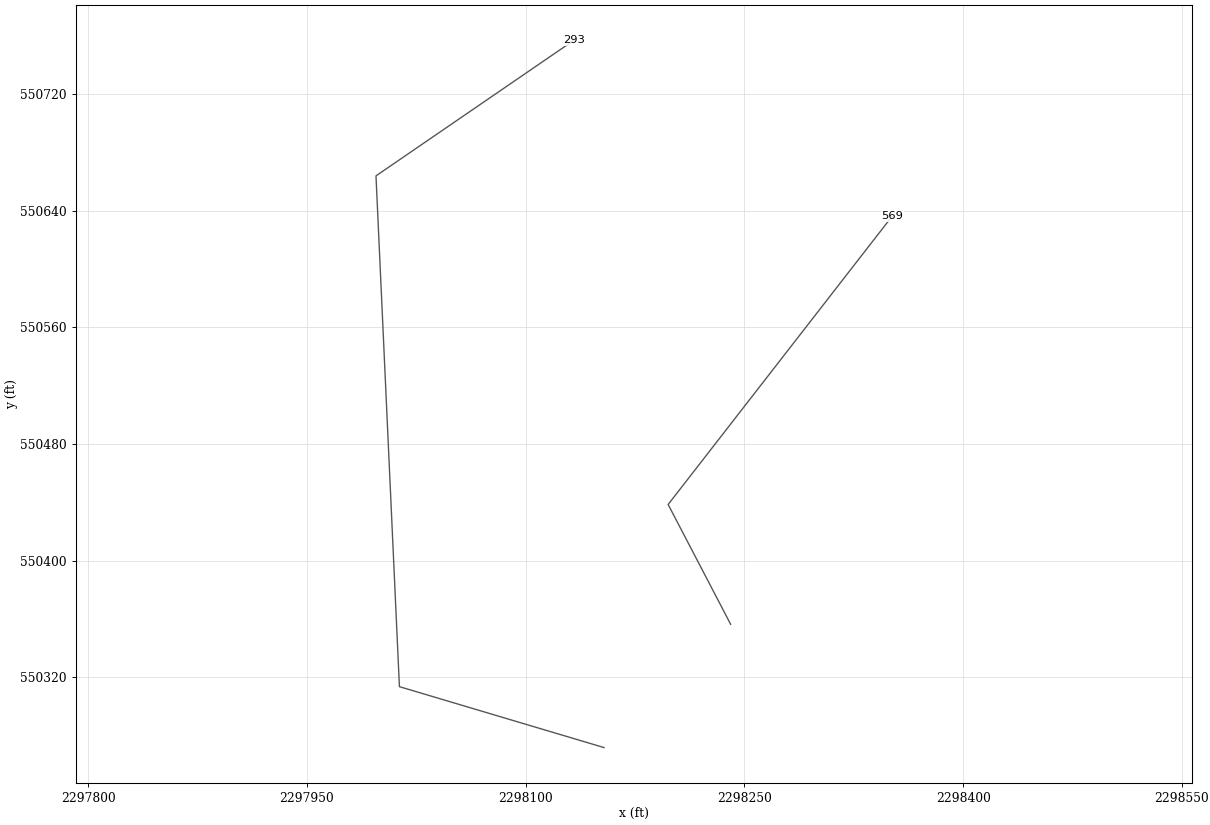
HEC-RAS study BRSHRN.prj: BRSHRN

--- BRSHRN.g01 (geometry) --- (continued)

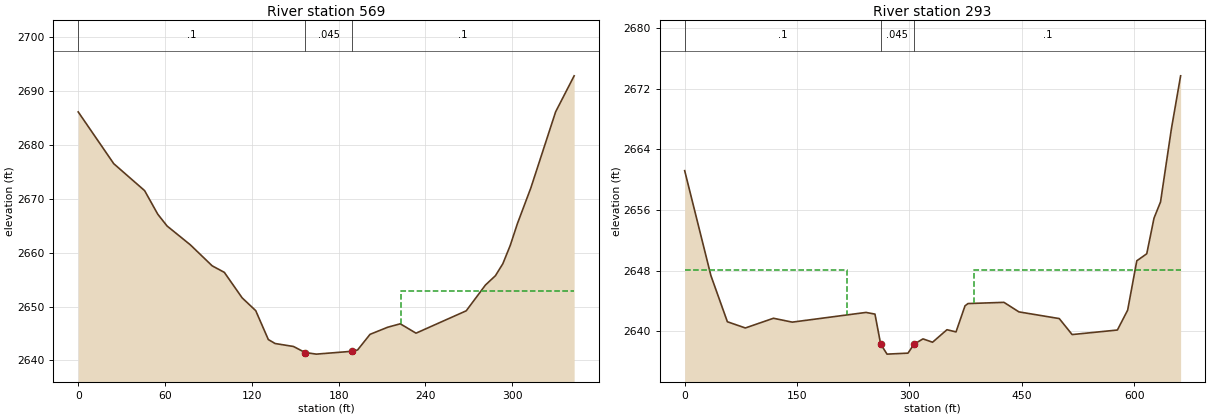
Type RM Length L Ch R = 1 ,569     ,264.2,275.9,291.3
XS GIS Cut Line= 3
2298240.58002307550356.4565142712298197.73241725550438.581092087
2298351.26967143550636.156163357
#Sta/Elev= 30
       0 2686.12    24.6  2676.5    45.9 2671.51      55 2667.13    61.4 2664.95
    77.5 2661.45    92.6 2657.55     101 2656.34   113.3 2651.61   122.7 2649.23
   131.4 2643.87   136.1 2643.13   148.8 2642.58   156.8 2641.46   164.6 2641.16
   189.32641.689   193.1 2641.93   201.7 2644.83   213.9 2646.15   222.6 2646.79
   233.5 2645.05   268.2  2649.2   281.5 2653.99   288.4 2655.72   293.5 2657.94
   298.6 2661.32   303.6  2665.4   312.9 2672.04     330 2686.14   342.8 2692.82
#Mann= 3 ,-1,0
       0      .1       0   156.8    .045       0   189.3      .1       0
#XS Ineff= 2 , 0
                          222.77         2652.87
Permanent Ineff=
       F       F
Bank Sta=156.8,189.3
XS Rating Curve= 0 ,0
Exp/Cntr(USF)=0,0
Exp/Cntr=0.3,0.1

Type RM Length L Ch R = 1 ,293     ,,,
XS GIS Cut Line= 4
2298153.77946113550271.8818282472298013.45355208550313.658243919
 2297997.3856999550663.9374214762298133.42684837550757.130964129
#Sta/Elev= 30
       0  2661.2    35.1 2647.33      57 2641.27      81 2640.45   118.5 2641.73
   143.6 2641.22     242  2642.5     254 2642.28   261.6 2638.33   270.1    2637
   298.1 2637.13   306.1 2638.31   318.1 2639.01   330.9 2638.57   350.1 2640.22
   362.2 2639.93   374.2 2643.37   378.2 2643.67   426.2 2643.83   446.2 2642.57
     500 2641.69   517.2 2639.58   577.6 2640.18   591.3  2642.8   603.5 2649.31
   616.8 2650.24   626.5 2654.94   635.2 2657.08   649.6 2666.66     662 2673.71
#Mann= 3 ,-1,0
       0      .1       0   261.6    .045       0   306.1      .1       0
#XS Ineff= 2 ,-1
       0  217.01 2648.12  385.77661.9607 2648.09
Permanent Ineff=
       F       F
Bank Sta=261.6,306.1
XS Rating Curve= 0 ,0
Exp/Cntr(USF)=0,0
Exp/Cntr=0.3,0.1
LCMann Table=0

Chan Stop Cuts=-1
Use User Specified Reach Order=0
Composite Channel Slope=5